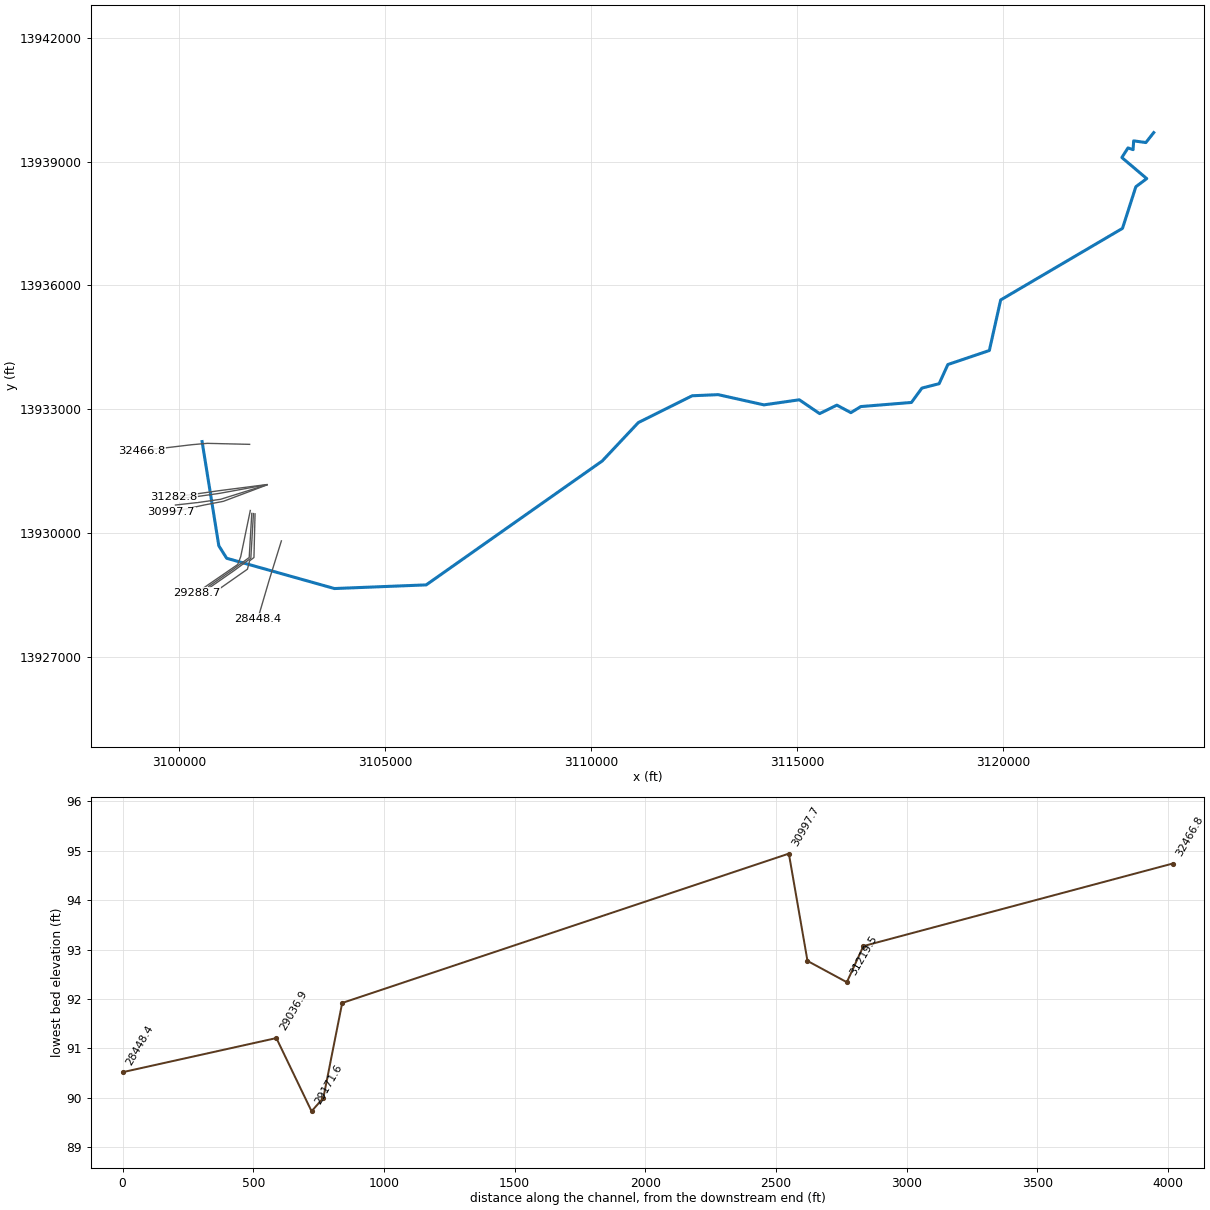
--- K111-00-00.prj (project) ---

Proj Title=K111-00-00
Current Plan=p03
Default Exp/Contr=0.3,0.1
English Units
Geom File=g02
Flow File=f10
Flow File=f09
Plan File=p08
Plan File=p03
Y Axis Title=Elevation
X Axis Title(PF)=Main Channel Distance
X Axis Title(XS)=Station
BEGIN DESCRIPTION:
 Cypress Creek Watershed
Turkey Creek
HCFCD Unit K111-00-00
Flood Hazard Model
10, 2, 1, 0.2%
Filename K111-00-00
Prepared by:  Halff Associates  DATE:  March 26, 2004
Reviewed by:  _____________________  DATE:  __________________
STATUS (Final)
TROPICAL STORM ALLISON RECOVERY PROJECT
END DESCRIPTION:
DSS Export Rating Curves= 0
DSS Export Rating Curve Sorted= 0
DSS Export Volume Flow Curves= 0
DXF OffsetX= 0
DXF OffsetY= 0
DXF ScaleX= 1
DXF ScaleY= 10

--- K111-00-00.p03 (plan) ---

Plan Title=Effective MP 2013
Program Version=3.13
Short Identifier=Eff MP 2013
Geom File=g02
Flow File=f09
Subcritical Flow
K Sum by GR= 0
Std Step Tol= 0.01
Critical Tol= 0.01
Num of Std Step Trials= 20
Max Error Tol= 0.3
Flow Tol Ratio= 0.001
Split Flow NTrial= 30
Split Flow Tol= 0.02
Split Flow Ratio= 0.02
Log Output Level= 0
Friction Slope Method= 1
Unsteady Friction Slope Method= 2
Unsteady Bridges Friction Slope Method= 1
Parabolic Critical Depth
Global Vel Dist= 0 , 0 , 0
Global Log Level= 0
CheckData=True
Encroach Param=-1 ,0,0, 2
BEGIN DESCRIPTION:
FEMA Effective MP October 2013
END DESCRIPTION:
Computation Interval=1HOUR
Output Interval=1HOUR
Run HTab= 0
Run UNet= 0
Run PostProcess= 0
UNET Theta= 1
UNET Theta Warmup= 1
UNET ZTol= 0.02
UNET ZSATol= 0.1
UNET MxIter= 20
UNET MaxInSteps= 20
UNET DtIC= 0
UNET DtMin= 0
UNET MaxCRTS= 20
UNET WFStab= 2
UNET SFStab= 1
UNET WFX= 1
UNET SFX= 1
UNET DSS MLevel= 4
UNET DZMax Abort= 100
UNET Convert EG Bridges=-1
UNET Use Existing IB Tables=-1
UNET Froude Reduction=False
UNET Froude Limit= 1
UNET Froude Power= 10
Instantaneous Interval=1HOUR
Write IC File= 0
IC Time=0,,
Echo Input=False
Echo Output=False
Write Detailed= 0
Detailed Automatic Start=False, 10

--- K111-00-00.p08 (plan) ---

Plan Title=Effective FW 2013
Program Version=3.13
Short Identifier=Eff FW 2013
Geom File=g02
Flow File=f10
Subcritical Flow
K Sum by GR= 0
Std Step Tol= 0.01
Critical Tol= 0.01
Num of Std Step Trials= 20
Max Error Tol= 0.3
Flow Tol Ratio= 0.001
Split Flow NTrial= 30
Split Flow Tol= 0.02
Split Flow Ratio= 0.02
Log Output Level= 0
Friction Slope Method= 1
Unsteady Friction Slope Method= 2
Unsteady Bridges Friction Slope Method= 1
Parabolic Critical Depth
Global Vel Dist= 0 , 0 , 0
Global Log Level= 0
CheckData=True
Encroach Param=-1 ,0,0, 2
Encroach River=K111-00-00
Encroach Reach=K111-00-00_0026
Encroach Node=32466.8
       1  4957.4  5044.5
Encroach Node=31282.8
       1  4957.1    5057
Encroach Node=31219.5
       1    4943    5073
Encroach Node=31139.7
       1    4943    5073
Encroach Node=31069.0
       1    4943    5073
Encroach Node=30997.7
       1  4927.7    5053
Encroach Node=29288.7
       1  4955.9  5045.6
Encroach Node=29216.6
       1  4940.1  5046.3
Encroach Node=29194.1
       1  4940.1  5046.3
Encroach Node=29171.6
       1  4940.1  5046.3
Encroach Node=29036.9
       1  4948.2  5035.8
Encroach Node=28448.4
       1  4955.7  5049.9
Encroach Node=27555.3
       1  4953.2  5045.7
Encroach Node=26371.8
       1  4953.2  5045.2
Encroach Node=25391.9
       1    4949  5039.6
Encroach Node=25305.2
       1  4943.6  5067.2
Encroach Node=25271.2
       1  4943.6  5067.2
Encroach Node=25237.2
       1  4943.6  5067.2
Encroach Node=25153.8
       1  4957.9  5045.8
Encroach Node=24264.
       1  4918.6  5058.6
Encroach Node=24138.2
       1 4951.15 5043.65
Encroach Node=24127.7
       1 4951.15 5043.65
Encroach Node=24117.2
       1 4951.15 5043.65
Encroach Node=24003.
       1  4951.8  5091.8
Encroach Node=23696.
       1  4950.3  5070.3
Encroach Node=23597.2
       1  4923.4  5063.5
Encroach Node=23586.7
       1  4923.4  5063.5
Encroach Node=23576.6
       1  4923.4  5063.5
Encroach Node=23289.
       1  4844.2  5091.3
Encroach Node=22305.
       1    4921  5119.7
Encroach Node=22189.1
       1  4914.6  5102.5
Encroach Node=22126.7
       1  4914.6  5102.5
Encroach Node=22071.3
       1  4914.6  5102.5
Encroach Node=21981.1
       1  4895.9  5081.2
Encroach Node=21898.0
       1  4899.8  5090.3
Encroach Node=21806.1
       1    4927    5061
Encroach Node=21777.6
       1    4927    5061
Encroach Node=21749.2
       1    4927    5061
Encroach Node=21724.5
       1  4941.4  5059.9
Encroach Node=21694.0
       1  4941.4  5059.9
Encroach Node=21663.5
       1  4941.4  5059.9
Encroach Node=21631.1
       1 4900.83 5087.93
Encroach Node=21620.0
       1 4900.83 5087.93
Encroach Node=21608.8
       1 4900.83 5087.93
Encroach Node=21487.8
       1  4891.1  5075.8
Encroach Node=20580.1
       1  4915.7    5085
Encroach Node=19179.9
       1  4912.5  5050.5
Encroach Node=19123.1
       1 4918.01 5078.61
Encroach Node=19111.6
       1 4918.01 5078.61
Encroach Node=19100.0
       1 4918.01 5078.61
Encroach Node=18983.0
       1    4926  5059.7
Encroach Node=17780.2
       1  4926.3  5056.9
Encroach Node=16662.8
       1  4936.6  5068.6
Encroach Node=15542.9
       1  4930.9  5058.6
Encroach Node=14378.1
       1  4919.2  5058.1
Encroach Node=13667.
       1  4924.2  5104.2
Encroach Node=13544.8
       1  4947.8  5058.1
Encroach Node=13490.2
       1  4947.8  5058.1
Encroach Node=13424.6
       1  4947.8  5058.1
Encroach Node=13319.5
       1  4924.8  5044.8
Encroach Node=13241.0
       1  4919.4  5061.8
Encroach Node=13182.2
       1  4928.7  5085.9
Encroach Node=13115.6
       1  4928.7  5085.9
Encroach Node=12915.
       1  4928.3  5084.9
Encroach Node=12154.9
       1  4952.9    5089
Encroach Node=10449.1
       1  4946.6  5080.8
Encroach Node=10291.5
       1  4939.7  5068.8
Encroach Node=9214.8
       1  4929.2  5059.3
Encroach Node=9116.8
       1  4943.4    5087
Encroach Node=9106.3
       1  4909.6  5111.8
Encroach Node=9095.8
       1  4909.6  5111.8
Encroach Node=9032.4
       1 4243.18  4451.8
Encroach Node=9000.4
       1 4243.18  4451.8
Encroach Node=8968.4
       1 4243.18  4451.8
Encroach Node=8906.6
       1 4246.71 4418.79
Encroach Node=8895.3
       1 4246.71 4418.79
Encroach Node=8884.0
       1 4246.71 4418.79
Encroach Node=8809.3
       1  4911.3  5079.5
Encroach Node=7789.
       1 4910.26 5111.44
Encroach Node=7689.5
       1 4910.16 5114.56
Encroach Node=7678.3
       1 4910.16 5114.56
Encroach Node=7667.0
       1 4910.16 5114.56
Encroach Node=7597.6
       1  4939.9    5060
Encroach Node=7538.1
       1  4939.9    5060
Encroach Node=7498.5
       1  4939.9    5060
Encroach Node=7377.2
       1    4902  5089.4
Encroach Node=6273.3
       1  4910.7  5130.7
Encroach Node=5396.5
       1    4910    5080
Encroach Node=3728.8
       1  4887.1    5088
Encroach Node=2842.5
       1  4830.2 5093.22
Encroach Node=2574.0
       1    4674    5094
BEGIN DESCRIPTION:
FEMA Effective Floodway October 2013
END DESCRIPTION:
Computation Interval=1HOUR
Output Interval=1HOUR
Run HTab= 0
Run UNet= 0
Run PostProcess= 0
UNET Theta= 1
UNET Theta Warmup= 1
UNET ZTol= 0.02
UNET ZSATol= 0.1
UNET MxIter= 20
UNET MaxInSteps= 20
UNET DtIC= 0
UNET DtMin= 0
UNET MaxCRTS= 20
UNET WFStab= 2
UNET SFStab= 1
UNET WFX= 1
UNET SFX= 1
UNET DSS MLevel= 4
UNET DZMax Abort= 100
UNET Convert EG Bridges=-1
UNET Use Existing IB Tables=-1
UNET Froude Reduction=False
UNET Froude Limit= 1
UNET Froude Power= 10
Instantaneous Interval=1HOUR
Write IC File= 0
IC Time=0,,
Echo Input=False
Echo Output=False
Write Detailed= 0
Detailed Automatic Start=False, 10

--- K111-00-00.f09 (steady flow) ---

Flow Title=Effective MP 2014
Program Version=3.13
Number of Profiles= 4
Profile Names=10PCT_10yr,2PCT_50yr,1PCT_100yr,0.2PCT_500yr
River Rch & RM=K111-00-00,K111-00-00_0026       ,32466.8
     580     860    1060    1530
River Rch & RM=K111-00-00,K111-00-00_0026       ,31282.8
     676    1007    1233    1779
River Rch & RM=K111-00-00,K111-00-00_0026       ,29288.7
     830    1244    1507    2175
River Rch & RM=K111-00-00,K111-00-00_0026       ,28448.4
     883    1325    1601    2310
River Rch & RM=K111-00-00,K111-00-00_0026       ,27555.3
     969    1459    1755    2532
River Rch & RM=K111-00-00,K111-00-00_0026       ,26371.8
    1096    1657    1982    2859
River Rch & RM=K111-00-00,K111-00-00_0026       ,25391.9
    1245    1889    2246    3239
River Rch & RM=K111-00-00,K111-00-00_0026       ,24264.
    1404    2137    2527    3645
River Rch & RM=K111-00-00,K111-00-00_0026       ,23696.
    1513    2308    2720    3922
River Rch & RM=K111-00-00,K111-00-00_0026       ,22305.
    1756    2691    3149    4542
River Rch & RM=K111-00-00,K111-00-00_0026       ,21724.5
    1842    2835    3317    4788
River Rch & RM=K111-00-00,K111-00-00_0026       ,19179.9
    1961    3035    3550    5129
River Rch & RM=K111-00-00,K111-00-00_0026       ,17780.2
    2055    3195    3735    5402
River Rch & RM=K111-00-00,K111-00-00_0026       ,16662.8
    2243    3514    4107    5949
River Rch & RM=K111-00-00,K111-00-00_0026       ,14378.1
    2426    3827    4469    6484
River Rch & RM=K111-00-00,K111-00-00_0026       ,13319.5
    2561    4060    4741    6884
River Rch & RM=K111-00-00,K111-00-00_0026       ,10449.1
    2755    4396    5130    7460
River Rch & RM=K111-00-00,K111-00-00_0026       ,9214.8
    2919    4682    5462    7952
River Rch & RM=K111-00-00,K111-00-00_0026       ,7789.
    3811    6129    7186   10497
River Rch & RM=K111-00-00,K111-00-00_0026       ,7377.2
    3963    6452    7553   11097
River Rch & RM=K111-00-00,K111-00-00_0026       ,3728.8
    4166    6892    8051   11916
Boundary for River Rch & Prof#=K111-00-00,K111-00-00_0026       , 1
Up Type= 0
Dn Type= 3
Dn Slope=0.0029
Boundary for River Rch & Prof#=K111-00-00,K111-00-00_0026       , 2
Up Type= 0
Dn Type= 3
Dn Slope=0.0029
Boundary for River Rch & Prof#=K111-00-00,K111-00-00_0026       , 3
Up Type= 0
Dn Type= 3
Dn Slope=0.0029
Boundary for River Rch & Prof#=K111-00-00,K111-00-00_0026       , 4
Up Type= 0
Dn Type= 3
Dn Slope=0.0029
DSS Import GetInterval= 0
DSS Import GetPeak= 0
DSS Import FillOption= 0

--- K111-00-00.f10 (steady flow) ---

Flow Title=Effective FW 2014
Program Version=3.13
Number of Profiles= 2
Profile Names=1PCT_100yr,1PCTFloodway_10
River Rch & RM=K111-00-00,K111-00-00_0026       ,32466.8
    1060    1060
River Rch & RM=K111-00-00,K111-00-00_0026       ,31282.8
    1233    1233
River Rch & RM=K111-00-00,K111-00-00_0026       ,29288.7
    1507    1507
River Rch & RM=K111-00-00,K111-00-00_0026       ,28448.4
    1601    1601
River Rch & RM=K111-00-00,K111-00-00_0026       ,27555.3
    1755    1755
River Rch & RM=K111-00-00,K111-00-00_0026       ,26371.8
    1982    1982
River Rch & RM=K111-00-00,K111-00-00_0026       ,25391.9
    2246    2246
River Rch & RM=K111-00-00,K111-00-00_0026       ,24264.
    2527    2527
River Rch & RM=K111-00-00,K111-00-00_0026       ,23696.
    2720    2720
River Rch & RM=K111-00-00,K111-00-00_0026       ,22305.
    3149    3149
River Rch & RM=K111-00-00,K111-00-00_0026       ,21724.5
    3317    3317
River Rch & RM=K111-00-00,K111-00-00_0026       ,19179.9
    3550    3550
River Rch & RM=K111-00-00,K111-00-00_0026       ,17780.2
    3735    3735
River Rch & RM=K111-00-00,K111-00-00_0026       ,16662.8
    4107    4107
River Rch & RM=K111-00-00,K111-00-00_0026       ,14378.1
    4469    4469
River Rch & RM=K111-00-00,K111-00-00_0026       ,13319.5
    4741    4741
River Rch & RM=K111-00-00,K111-00-00_0026       ,10449.1
    5130    5130
River Rch & RM=K111-00-00,K111-00-00_0026       ,9214.8
    5462    5462
River Rch & RM=K111-00-00,K111-00-00_0026       ,7789.
    7186    7186
River Rch & RM=K111-00-00,K111-00-00_0026       ,7377.2
    7553    7553
River Rch & RM=K111-00-00,K111-00-00_0026       ,3728.8
    8051    8051
Boundary for River Rch & Prof#=K111-00-00,K111-00-00_0026       , 1
Up Type= 0
Dn Type= 1
Dn Known WS=69.79
Boundary for River Rch & Prof#=K111-00-00,K111-00-00_0026       , 2
Up Type= 0
Dn Type= 1
Dn Known WS=70.79
DSS Import GetInterval= 0
DSS Import GetPeak= 0
DSS Import FillOption= 0

--- K111-00-00.g02 (geometry) ---

Geom Title=K111-00-00 2013
Program Version=3.13

River Reach=K111-00-00      ,K111-00-00_0026
Reach XY= 30
      3100565.78     13932213.61      3100971.47      13929686.6
      3101162.04     13929384.49        3103776.       13928650.
      3106000.99     13928738.68      3110270.08     13931743.02
      3111145.95     13932674.45      3112452.38     13933324.62
      3113081.72     13933351.53      3114191.35     13933103.87
       3115050.1     13933226.87      3115542.78      13932891.6
      3115960.19     13933097.19      3116301.33      13932914.9
      3116541.44      13933062.6      3117769.22      13933162.3
      3118023.56     13933510.39      3118441.09     13933617.16
       3118652.5       13934082.        3119659.       13934422.
      3119933.28     13935647.54      3122888.14     13937383.65
      3123211.92      13938393.2      3123475.81     13938590.25
      3122872.51     13939101.53      3123020.95     13939334.17
      3123145.08      13939292.5      3123158.97     13939505.18
      3123454.98     13939464.38      3123645.95      13939705.7

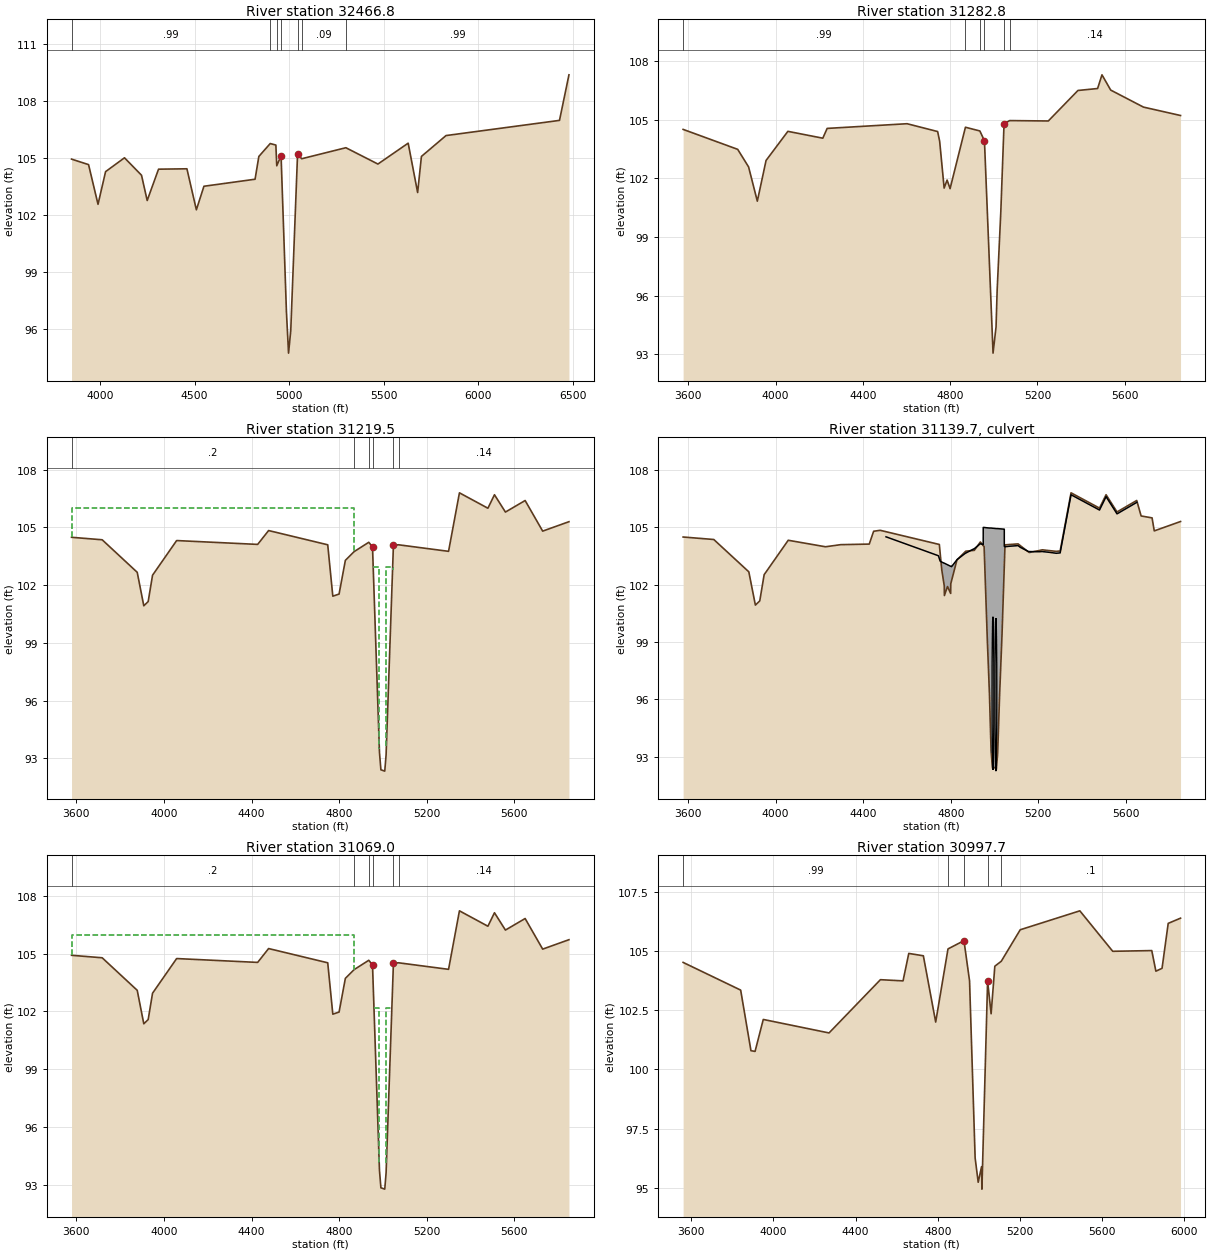
Type RM Length L Ch R = 1 ,32466.8 ,1184,1184,1185
BEGIN DESCRIPTION:
Cross Section K111-00-00-X16
END DESCRIPTION:
XS GIS Cut Line= 4
       3101719.2     13932146.46      3100692.59     13932170.82
      3100311.23     13932137.17 3099099.802731213931992.9864459
#Sta/Elev= 30
  3849.6  104.96  3939.6  104.67  3989.6  102.58  4029.6   104.3  4129.6  105.03
  4219.6  104.11  4249.6  102.78  4309.6  104.43  4459.6  104.45  4509.6  102.29
  4549.6  103.53  4819.9   103.9  4839.9   105.1    4900  105.78  4929.9   105.7
  4934.6  104.61  4957.4  105.14  4985.7   96.93  4996.9   94.74  5008.6   95.92
  5044.5  105.21  5066.7  104.98    5300  105.56  5469.4   104.7  5629.4   105.8
  5679.4   103.2  5699.4   105.1  5829.4   106.2  6429.4     107  6479.4   109.4
#Mann= 7 ,-1 , 0
  3849.6     .99       0    4900      .1       0  4934.6    .045       0
  4957.4     .04       0  5044.5    .045       0  5066.7     .09       0
    5300     .99       0
Bank Sta=4957.4,5044.5
Exp/Cntr=0.3,0.1

Type RM Length L Ch R = 1 ,31282.8 ,63.3,63.3,63
BEGIN DESCRIPTION:
Cross Section K111-00-00-X17b
END DESCRIPTION:
XS GIS Cut Line= 4
      3102137.01     13931171.61      3100971.15     13931021.93
      3100492.25     13930953.75      3099877.35      13930874.1
#Sta/Elev= 30
  3576.4  104.51  3826.4  103.49  3876.4  102.59  3916.4  100.84  3956.4  102.92
  4056.4  104.41  4216.4  104.06  4236.4  104.56  4602.6   104.8  4742.6   104.4
  4751.9   103.9  4772.4  101.51  4785.9  101.92  4799.6  101.48    4870  104.62
    4936  104.43  4957.1  103.93  4996.5   93.07  5010.2   94.41  5015.3   96.29
  5032.1  100.31  5046.9   104.8  5072.7  104.96  5249.7  104.94  5385.6   106.5
  5475.6   106.6  5495.6   107.3  5535.6  106.52  5685.6  105.65  5855.6  105.22
#Mann= 6 ,-1 , 0
  3576.4     .99       0    4870      .1       0    4936    .045       0
  4957.1     .04       0  5046.9    .045       0  5072.7     .14       0
Bank Sta=4957.1,5046.9
Exp/Cntr=0.5,0.3

Type RM Length L Ch R = 1 ,31219.5 ,150.5,150.5,150.5
BEGIN DESCRIPTION:
Upstream Section of Bridge/Culvert/Weir
END DESCRIPTION:
XS GIS Cut Line= 4
      3102138.79     13931168.06      3100986.95      13930957.9
      3100461.49     13930883.07      3099895.09      13930819.3
#Sta/Elev= 30
    3578  104.49    3718  104.36    3878  102.67    3908  100.93    3928  101.15
    3948  102.52    4058  104.32    4428  104.12    4478  104.84    4748   104.1
  4771.2  101.43  4799.8  101.54  4828.5  103.29    4868  103.74  4935.4  104.23
  4952.5  103.99  4984.3   93.31  4990.8   92.41  5008.4   92.34  5014.5   93.18
    5048  104.08  5071.4   104.1  5299.8  103.76  5349.5   106.8  5479.5     106
  5509.5   106.7  5559.5   105.8  5649.5   106.4  5729.6  104.81  5849.6   105.3
#Mann= 6 ,-1 , 0
    3578      .2       0    4868     .09       0  4935.4    .045       0
  4952.5     .04       0    5048    .045       0  5071.4     .14       0
#XS Ineff= 3 ,-1
    3578    4868     106    4955 4983.76  102.94    5016    5044  102.94
Permanent Ineff=
       T       F       F
Bank Sta=4952.5,5048
Exp/Cntr=0.5,0.3

Type RM Length L Ch R = 2 ,31139.7 ,,,
BEGIN DESCRIPTION:
NORTH VISTA; Inverted culvert based on field survey data VRR
Structure ID: K111-00-00-S17
END DESCRIPTION:
Bridge Culvert--1,0,-1,-1, 0
Deck Dist Width WeirC Skew NumUp NumDn MinLoCord MaxHiCord MaxSubmerge Is_Ogee
10,121.5,3,0, 54, 54, , , 0.95, 0, ,,,
  4504.5  4698.2  4743.9  4751.4  4751.6  4759.3  4770.5  4771.2  4785.3  4799.8
  4800.3  4803.8  4828.5  4829.1    4868  4868.7  4870.7  4903.8  4907.7  4935.4
 4948.39  4948.5 4948.61  4952.5  4967.3  4976.9  4984.3  4990.8    5001  5008.4
  5014.5  5023.2  5034.2 5044.59  5044.7 5044.81    5048    5071  5071.4  5107.6
  5115.7  5116.4  5155.2  5159.1  5203.1  5218.1  5249.4  5282.1  5299.8  5349.5
  5479.5  5509.5  5559.5  5649.5
   104.5   103.7  103.51  103.24  103.23  103.18  103.12  103.12  103.04  102.96
  102.96  102.94   103.3  103.31  103.65  103.66  103.66  103.86  103.88  104.14
  104.09  104.99  104.99  104.99  104.97  104.96  104.96  104.95  104.94  104.93
  104.93  104.92  104.91   104.9   104.9     104  103.98  104.01  104.01  104.04
  103.97  103.96  103.73  103.73  103.72  103.73  103.69  103.64  103.66   106.7
   105.9   106.6   105.7   106.3
   104.5  103.69   103.5  103.23  103.22  102.66  101.84  101.33   101.8  101.44
  101.95   102.1  103.19   103.2  103.64  103.65  103.65  103.69  103.69  104.13
  103.95  103.95  103.94  103.89   98.97   96.18   93.21   92.31   92.34   92.24
   93.08   96.09   99.24  102.81  102.85  102.88  103.98     104     104  104.03
  103.96  103.95  103.61  103.58  103.68  103.72  103.68  103.64  103.66   106.7
   105.9   106.6   105.7   106.3
  4504.5  4698.2  4743.9  4751.4  4751.6  4759.3  4770.5  4771.2  4785.3  4799.8
  4800.3  4803.8  4828.5  4829.1    4868  4868.7  4870.7  4903.8  4907.7  4935.4
 4948.39  4948.5 4948.61  4952.5  4967.3  4976.9  4984.3  4990.8    5001  5008.4
  5014.5  5023.2  5034.2 5044.59  5044.7 5044.81    5048    5071  5071.4  5107.6
  5115.7  5116.4  5155.2  5159.1  5203.1  5218.1  5249.4  5282.1  5299.8  5349.5
  5479.5  5509.5  5559.5  5649.5
  104.72  103.91  103.72  103.45  103.44  103.18  103.12  103.12  103.04  102.96
  102.96  102.94  103.41  103.42  103.86  103.87  103.87  103.91  103.91  104.35
  104.17  104.99  104.99  104.99  104.97  104.96  104.96  104.95  104.94  104.93
  104.93  104.92  104.91   104.9   104.9     104   104.2  104.22  104.22  104.25
  104.18  104.17  103.83   103.8   103.9  103.94   103.9  103.86  103.88  106.92
  106.12  106.82  105.92  106.52
  104.72  103.91  103.72  103.45  103.44  102.88  102.06  101.55  102.02  101.66
  102.17  102.32  103.41  103.42  103.86  103.87  103.87  103.91  103.91  104.35
  104.17  104.17  104.16  104.11   99.19    96.4   93.43   92.53   92.56   92.46
    93.3   96.31   99.46  103.03  103.07   103.1   104.2  104.22  104.22  104.25
  104.18  104.17  103.83   103.8   103.9  103.94   103.9  103.86  103.88  106.92
  106.12  106.82  105.92  106.52
BR Coef= 1 , 0 , 0 ,1.25, 0 ,,,0.8,-1,2,0,
WSPro=,,,, 1 ,,,, 0 ,,,, 0 ,,,,-1 ,-1 ,-1 , 0 , 0 , 0 , 0 , 0
Culvert=1,8,,121.5,0.015,0.2,1,1,1,92.32,4993,92.5,4993,Culvert #1  , 0 ,10
Culvert Bottom n=0.015
Culvert=1,8,,121.5,0.015,0.2,1,1,1,92.25,5006.4,92.18,5006.4,Culvert #2  , 0 ,10
Culvert Bottom n=0.015
BR U #Sta/Elev= 66
    3578  104.49    3718  104.36    3878  102.67    3908  100.93    3928  101.15
    3948  102.52    4058  104.32    4228  103.98    4298  104.09    4428  104.12
    4448  104.79    4478  104.84    4748   104.1  4759.3  102.76  4770.5  101.94
  4771.2  101.43  4785.3   101.9  4799.8  101.54  4800.3  102.05  4803.8   102.2
  4828.5  103.29  4829.1   103.3    4868  103.74  4868.7  103.75  4870.7  103.75
  4903.8  103.79  4907.7  103.79  4935.4  104.23 4948.39  104.05  4948.5  104.05
 4948.61  104.04  4952.5  103.99  4967.3   99.07  4976.9   96.28  4984.3   93.31
  4990.8   92.41    5001   92.44  5008.4   92.34  5014.5   93.18  5023.2   96.19
  5034.2   99.34 5044.59  102.91  5044.7  102.95 5044.81  102.98    5048  104.08
    5071   104.1  5071.4   104.1  5107.6  104.13  5115.7  104.06  5116.4  104.05
  5155.2  103.71  5159.1  103.68  5203.1  103.78  5218.1  103.82  5249.4  103.78
  5282.1  103.74  5299.8  103.76  5349.5   106.8  5479.5     106  5509.5   106.7
  5559.5   105.8  5649.5   106.4  5669.6  105.59  5719.6  105.49  5729.6  104.81
  5849.6   105.3
BR U #Mann= 6
    3578      .2    4868     .09  4935.4    .045  4952.5     .04    5048    .045
  5071.4     .14
BR D #Sta/Elev= 66
    3578  104.92    3718  104.79    3878   103.1    3908  101.36    3928  101.58
    3948  102.95    4058  104.75    4228  104.41    4298  104.52    4428  104.55
    4448  105.22    4478  105.27    4748  104.53  4759.3  103.19  4770.5  102.37
  4771.2  101.86  4785.3  102.33  4799.8  101.97  4800.3  102.48  4803.8  102.63
  4828.5  103.72  4829.1  103.73    4868  104.17  4868.7  104.18  4870.7  104.18
  4903.8  104.22  4907.7  104.22  4935.4  104.66 4948.39  104.48  4948.5  104.48
 4948.61  104.47  4952.5  104.42  4967.3    99.5  4976.9   96.71  4984.3   93.74
  4990.8   92.84    5001   92.87  5008.4   92.77  5014.5   93.61  5023.2   96.62
  5034.2   99.77 5044.59  103.34  5044.7  103.38 5044.81  103.41    5048  104.51
    5071  104.53  5071.4  104.53  5107.6  104.56  5115.7  104.49  5116.4  104.48
  5155.2  104.14  5159.1  104.11  5203.1  104.21  5218.1  104.25  5249.4  104.21
  5282.1  104.17  5299.8  104.19  5349.5  107.23  5479.5  106.43  5509.5  107.13
  5559.5  106.23  5649.5  106.83  5669.6  106.02  5719.6  105.92  5729.6  105.24
  5849.6  105.73
BR D #Mann= 6
    3578      .2    4868     .09  4935.4    .045  4952.5     .04    5048    .045
  5071.4     .14
BC Design=,, 0 ,, 0 ,,,,,,
BC HTab HWMax=106.8

Type RM Length L Ch R = 1 ,31069.0 ,71.3,71.3,71.25
BEGIN DESCRIPTION:
Downstream Section of Bridge/Culvert/Weir
END DESCRIPTION:
XS GIS Cut Line= 4
      3102139.38     13931166.28      3101013.95     13930813.94
      3100486.84     13930738.88        3099920.       13930675.
#Sta/Elev= 30
    3578  104.92    3718  104.79    3878   103.1    3908  101.36    3928  101.58
    3948  102.95    4058  104.75    4428  104.55    4478  105.27    4748  104.53
  4771.2  101.86  4799.8  101.97  4828.5  103.72    4868  104.17  4935.4  104.66
  4952.5  104.42  4984.3   93.74  4990.8   92.84  5008.4   92.77  5014.5   93.61
    5048  104.51  5071.4  104.53  5299.8  104.19  5349.5  107.23  5479.5  106.43
  5509.5  107.13  5559.5  106.23  5649.5  106.83  5729.6  105.24  5849.6  105.73
#Mann= 6 ,-1 , 0
    3578      .2       0    4868     .09       0  4935.4    .045       0
  4952.5     .04       0    5048    .045       0  5071.4     .14       0
#XS Ineff= 3 ,-1
    3578    4868     106    4959 4983.47   102.2 5016.07    5042   102.2
Permanent Ineff=
       T       F       F
Bank Sta=4952.5,5048
Exp/Cntr=0.5,0.3

Type RM Length L Ch R = 1 ,30997.7 ,1653,1709,1756
BEGIN DESCRIPTION:
Cross Section K111-00-00-X17A
END DESCRIPTION:
XS GIS Cut Line= 4
      3102138.79     13931162.14      3101082.08     13930764.98
      3100628.95     13930678.17      3099817.87      13930501.8
#Sta/Elev= 30
  3561.2  104.52  3841.2  103.35  3891.2  100.79  3911.2  100.76  3951.2  102.11
  4271.2  101.54  4521.2  103.79  4631.2  103.74  4659.2   104.9  4730.1   104.8
  4790.1     102    4850  105.09  4927.7  105.44  4954.9  103.74    4982   96.26
    4997   95.23  5013.3   95.89    5015   94.94  5042.7  103.73  5059.8  102.35
  5077.9  104.36  5109.3  104.57  5201.5   105.9  5491.5   106.7  5651.5  104.99
  5841.5  105.02  5861.5  104.15  5891.5  104.27  5921.5  106.17  5981.5  106.39
#Mann= 5 ,-1 , 0
  3561.2     .99       0    4850      .1       0  4927.7     .04       0
  5042.7    .045       0  5109.3      .1       0
Bank Sta=4927.7,5042.7
Exp/Cntr=0.3,0.1

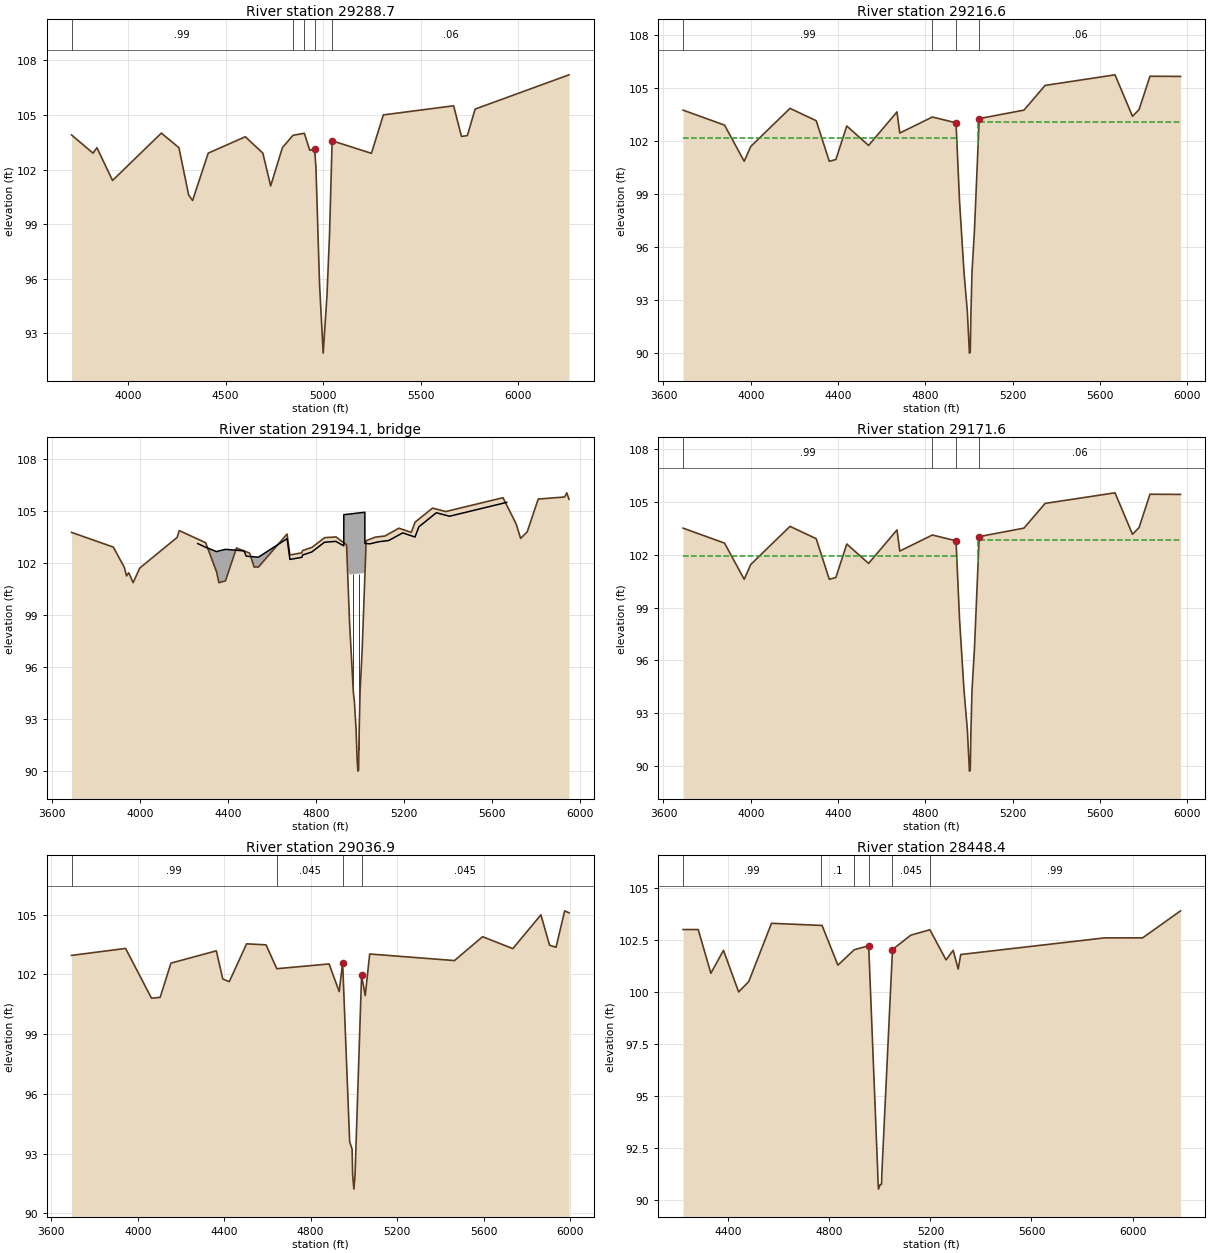
Type RM Length L Ch R = 1 ,29288.7 ,92,72.1,22
BEGIN DESCRIPTION:
Cross Section K111-00-00-X16b
END DESCRIPTION:
XS GIS Cut Line= 4
      3101734.85     13930542.76      3101502.41     13929422.93
      3101429.73     13929232.86      3100439.71     13928553.17
#Sta/Elev= 30
  3710.8   103.9  3820.8   102.9  3840.8   103.2  3920.8   101.4  4170.8     104
  4260.8   103.2  4310.8   100.6  4330.8   100.3  4410.8   102.9  4600.8   103.8
  4690.8   102.9  4730.8   101.1  4790.8   103.2    4845  103.88  4903.5  103.99
  4930.8  103.06  4955.9  103.13  4962.7  102.12    4981   95.74  4999.8   91.92
  5019.1   95.08  5032.2   98.41  5045.6  103.58  5246.8  102.89    5308     105
    5668   105.5    5708  103.82    5738  103.86    5778  105.32  6258.9   107.2
#Mann= 5 ,-1 , 0
  3710.8     .99       0    4845      .1       0  4903.5    .045       0
  4955.9     .04       0  5045.6     .06       0
Bank Sta=4955.9,5045.6
Exp/Cntr=0.5,0.3

Type RM Length L Ch R = 1 ,29216.6 ,45,45,45
BEGIN DESCRIPTION:
Upstream Section of Bridge/Culvert/Weir
END DESCRIPTION:
XS GIS Cut Line= 4
      3101770.76     13930472.12      3101708.26     13929402.67
      3101308.05     13929107.61      3100725.03      13928702.3
#Sta/Elev= 30
  3689.9  103.77  3879.9  102.92  3969.9  100.87  3999.9  101.71  4179.7  103.87
  4299.7  103.17  4359.7  100.87  4389.7  100.97  4439.7  102.87  4539.7  101.77
  4669.7  103.67  4682.5  102.47  4831.7  103.38  4940.1  103.05  4956.4   98.56
  4976.9   94.54  4991.8   92.38  5001.5      90  5005.3   90.07  5008.1   92.16
  5013.3    94.6  5024.5   96.95  5046.3  103.29  5251.3  103.77  5348.2  105.17
  5668.2  105.77  5748.4  103.42  5778.4   103.8  5828.4  105.69  5968.4  105.68
#Mann= 4 ,-1 , 0
  3689.9     .99       0  4831.7     .06       0  4940.1     .04       0
  5046.3     .06       0
#XS Ineff= 2 , 0
       0 4945.12  102.21 5041.11       0  103.11
Permanent Ineff=
       F       F
Bank Sta=4940.1,5046.3
Exp/Cntr=0.5,0.3

Type RM Length L Ch R = 3 ,29194.1 ,,,
BEGIN DESCRIPTION:
NORTHAIRE ROAD
Structure ID: K111-00-00-S16
END DESCRIPTION:
Bridge Culvert--1,0,-1,-1, 0
Deck Dist Width WeirC Skew NumUp NumDn MinLoCord MaxHiCord MaxSubmerge Is_Ogee
10,25,2.6,33, 34, 34, , , 0.95, 0, ,,,
 4263.91  4299.7 4349.71  4359.7  4389.7 4439.71 4473.91 4483.91 4499.71  4519.7
  4539.7  4669.7 4682.51    4737  4739.8 4782.11  4839.7  4891.4 4927.49 4927.58
 4938.07 4942.51 5022.55 5023.28 5023.37  5046.3  5086.9  5131.8  5195.2  5251.3
 5268.81 5348.21 5408.21  5668.2
  103.12  102.91  102.66   102.7  102.79  102.74   102.7   102.4  102.38  102.36
  102.34  103.41  102.21  102.33  102.46  102.64   103.2  103.25  102.99  104.79
  104.81  104.81  104.93  104.93  103.13  103.11  103.23   103.3  103.74   103.5
  104.09   104.9   104.7   105.5
  103.11   102.9   101.2   100.6   100.7   102.6  102.43  102.38   102.3   101.5
   101.5   103.4   102.2  102.32  102.45  102.63  103.19  103.24   102.9   102.9
  102.78  101.32  101.43  101.68  101.71  103.02  103.22  103.29  103.74   103.5
  104.09   104.9   104.7   105.5
  4179.7  4299.7 4349.71  4359.7  4389.7 4439.71 4473.91 4483.91 4499.71  4519.7
  4539.7  4669.7 4682.51    4737  4739.8 4782.11  4839.7  4891.4 4927.49 4927.58
 4938.07 4942.51 5022.55 5023.28 5023.37  5046.3  5086.9  5131.8  5195.2  5251.3
 5268.81 5348.21 5408.21  5668.2
   103.6  102.91  102.66   102.7  102.79  102.74   102.7   102.4  102.38  102.36
  102.34  103.41  102.21  102.33  102.46  102.64   103.2  103.25  102.99  104.79
  104.81  104.81  104.93  104.93  103.13  103.11  103.23   103.3  103.74   103.5
  104.09   104.9   104.7   105.5
  103.49  102.79  101.09  100.49  100.59  102.49  102.32  102.27  102.19  101.39
  101.39  103.29  102.09  102.21  102.34  102.52  103.08  103.13  102.79  102.79
  102.67  101.21  101.32  101.57   101.6  102.91  103.11  103.18  103.63  103.39
  103.98  104.79  104.59  105.39
Pier Skew, UpSta & Num, DnSta & Num=  ,4971, 2 ,4971, 2 , 0 , 0 , 0 ,,
     1.2     1.2
   93.21  102.35
     1.2     1.2
    93.1  102.24
Pier Skew, UpSta & Num, DnSta & Num=  ,4996, 2 ,4996, 2 , 0 , 0 , 0 ,,
     1.2     1.2
   89.46  102.39
     1.2     1.2
   89.35  102.28
BR Coef= 1 , 1 , 1 ,1.25, 0 ,,,0.8,0,2,0,
WSPro=,,,, 1 ,,,, 0 ,,,, 0 ,,,,-1 ,-1 ,-1 , 0 , 0 , 0 , 0 , 0
BR U #Sta/Elev= 78
  3689.9  103.77  3879.9  102.92  3929.9  101.75  3939.9  101.26  3949.9  101.44
  3969.9  100.87  3999.9  101.71  4169.9  103.48  4179.7  103.87  4263.9  103.38
  4299.7  103.17  4349.7  101.47  4359.7  100.87  4383.9  100.95  4389.7  100.97
  4439.7  102.87  4473.9   102.7  4483.9  102.65  4499.7  102.57  4519.7  101.77
  4539.7  101.77  4663.9  103.59  4669.7  103.67  4673.9  103.28  4682.5  102.47
  4683.9  102.47    4737  102.59  4739.8  102.72  4752.5  102.77  4762.5  102.82
  4782.1   102.9  4790.8  102.98  4831.7  103.38  4839.7  103.46  4846.2  103.47
    4886   103.5  4891.4  103.51  4905.2  103.38 4927.49  103.17  4927.6  103.17
 4927.71  103.17  4940.1  103.05 4944.47  101.61 4944.55  101.59 4953.78   98.56
 4970.98   94.54 4975.84   93.99 4983.48   92.38 4987.84   90.75 4991.62      90
  4994.8   90.07 4995.98   91.22 4997.15   92.16 5001.52    94.6 5010.91   96.95
 5024.62   101.7 5024.71  101.73 5025.25  101.92 5025.34  101.95 5025.44  101.98
  5029.2  103.29  5069.8  103.49  5080.4  103.51  5114.7  103.56  5134.3   103.7
  5178.1  104.01  5234.2  103.77  5251.7  104.36  5331.1  105.17  5391.1  104.97
  5651.1  105.77  5711.3  104.25  5731.3  103.42  5761.3   103.8  5811.3  105.69
  5931.3  105.81  5941.3  106.05  5951.3  105.68
BR U #Mann= 4
  3689.9     .99  4831.7     .06  4940.1     .04  5029.2     .06
BR U Banks=,5029.2
BR D #Sta/Elev= 78
  3689.9   103.5  3879.9  102.65  3929.9  101.48  3939.9  100.99  3949.9  101.17
  3969.9   100.6  3999.9  101.44  4169.9  103.21  4179.7   103.6  4263.9  103.11
  4299.7   102.9  4349.7   101.2  4359.7   100.6  4383.9  100.68  4389.7   100.7
  4439.7   102.6  4473.9  102.43  4483.9  102.38  4499.7   102.3  4519.7   101.5
  4539.7   101.5  4663.9  103.32  4669.7   103.4  4673.9  103.01  4682.5   102.2
  4683.9   102.2    4737  102.32  4739.8  102.45  4752.5   102.5  4762.5  102.55
  4782.1  102.63  4790.8  102.71  4831.7  103.11  4839.7  103.19  4846.2   103.2
    4886  103.23  4891.4  103.24  4905.2  103.11 4927.49   102.9  4927.6   102.9
 4927.71   102.9  4940.1  102.78 4944.47  101.34 4944.55  101.32 4953.78   98.29
 4970.98   94.27 4975.84   93.72 4983.48   92.11 4987.84   90.48 4991.62   89.73
  4994.8    89.8 4995.98   90.95 4997.15   91.89 5001.52   94.33 5010.91   96.68
 5024.62  101.43 5024.71  101.46 5025.25  101.65 5025.34  101.68 5025.44  101.71
  5029.2  103.02  5069.8  103.22  5080.4  103.24  5114.7  103.29  5134.3  103.43
  5178.1  103.74  5234.2   103.5  5251.7  104.09  5331.1   104.9  5391.1   104.7
  5651.1   105.5  5711.3  103.98  5731.3  103.15  5761.3  103.53  5811.3  105.42
  5931.3  105.54  5941.3  105.78  5951.3  105.41
BR D #Mann= 4
  3689.9     .99  4831.7     .06  4940.1     .04  5029.2     .06
BR D Banks=,5029.2
BC Design=,, 0 ,, 0 ,,,,,,
BC HTab HWMax=106.05

Type RM Length L Ch R = 1 ,29171.6 ,110,134.7,151
BEGIN DESCRIPTION:
Downstream Section of Bridge/Culvert/Weir
END DESCRIPTION:
XS GIS Cut Line= 4
      3101811.11      13930468.1      3101747.79     13929384.61
      3101335.91     13929080.96      3100752.55      13928675.4
#Sta/Elev= 30
  3689.9   103.5  3879.9  102.65  3969.9   100.6  3999.9  101.44  4179.7   103.6
  4299.7   102.9  4359.7   100.6  4389.7   100.7  4439.7   102.6  4539.7   101.5
  4669.7   103.4  4682.5   102.2  4831.7  103.11  4940.1  102.78  4956.4   98.29
  4976.9   94.27  4991.8   92.11  5001.5   89.73  5005.3    89.8  5008.1   91.89
  5013.3   94.33  5024.5   96.68  5046.3  103.02  5251.3   103.5  5348.2   104.9
  5668.2   105.5  5748.4  103.15  5778.4  103.53  5828.4  105.42  5968.4  105.41
#Mann= 4 ,-1 , 0
  3689.9     .99       0  4831.7     .06       0  4940.1     .04       0
  5046.3     .06       0
#XS Ineff= 2 , 0
       0 4945.12  101.94 5041.11       0  102.84
Permanent Ineff=
       F       F
Bank Sta=4940.1,5046.3
Exp/Cntr=0.5,0.3

Type RM Length L Ch R = 1 ,29036.9 ,592,588.5,588.5
BEGIN DESCRIPTION:
Cross Section K111-00-00-X16a
END DESCRIPTION:
XS GIS Cut Line= 5
        3101850.      13930461.3      3101823.43     13929402.09
      3101717.68     13929322.75      3101665.41     13929119.15
      3100928.15     13928602.83
#Sta/Elev= 30
  3693.7  102.96  3943.7  103.31  4063.7  100.81  4103.7  100.85  4153.7  102.57
  4363.7  103.19  4393.7  101.77  4423.7  101.64  4503.7  103.54  4593.7  103.49
  4643.7  102.29  4885.5  102.53  4932.2  101.14  4948.2  102.58  4980.7   93.59
    4992   93.22  4994.5   91.93  5000.2   91.21  5005.5    91.9  5035.8  101.96
  5052.7  100.94  5073.4  103.03  5465.7   102.7  5595.7   103.9  5735.7   103.3
  5865.7     105  5905.7  103.47  5935.7  103.37  5975.7   105.2  5995.7   105.1
#Mann= 4 ,-1 , 0
  3693.7     .99       0  4643.7    .045       0  4948.2     .04       0
  5035.8    .045       0
Bank Sta=4948.2,5035.8
Exp/Cntr=0.3,0.1

Type RM Length L Ch R = 1 ,28448.4 ,893.1,893.1,893
BEGIN DESCRIPTION:
Cross Section K111-00-00-X15
END DESCRIPTION:
XS GIS Cut Line= 4
      3102488.76     13929805.78      3102305.52     13929215.94
      3102189.28     13928842.24      3101918.81      13927921.1
#Sta/Elev= 29
    4221     103    4281     103    4331   100.9    4381     102    4441     100
    4481   100.5    4571   103.3    4765   103.2    4771   103.2  4833.8  101.29
  4898.7  102.03  4955.7  102.22  4990.8   91.55  4992.9   90.83  4994.5   90.52
  5001.1   90.74  5006.3   90.75    5007   90.93  5007.5   91.21  5049.9  102.04
  5122.4  102.73    5198  102.99  5261.9  101.54    5290     102    5310   101.1
    5320   101.8    5890   102.6    6040   102.6    6190   103.9
#Mann= 6 ,-1 , 0
    4221     .99       0    4765      .1       0  4898.7    .045       0
  4955.7     .04       0  5049.9    .045       0    5198     .99       0
Bank Sta=4955.7,5049.9
Exp/Cntr=0.3,0.1