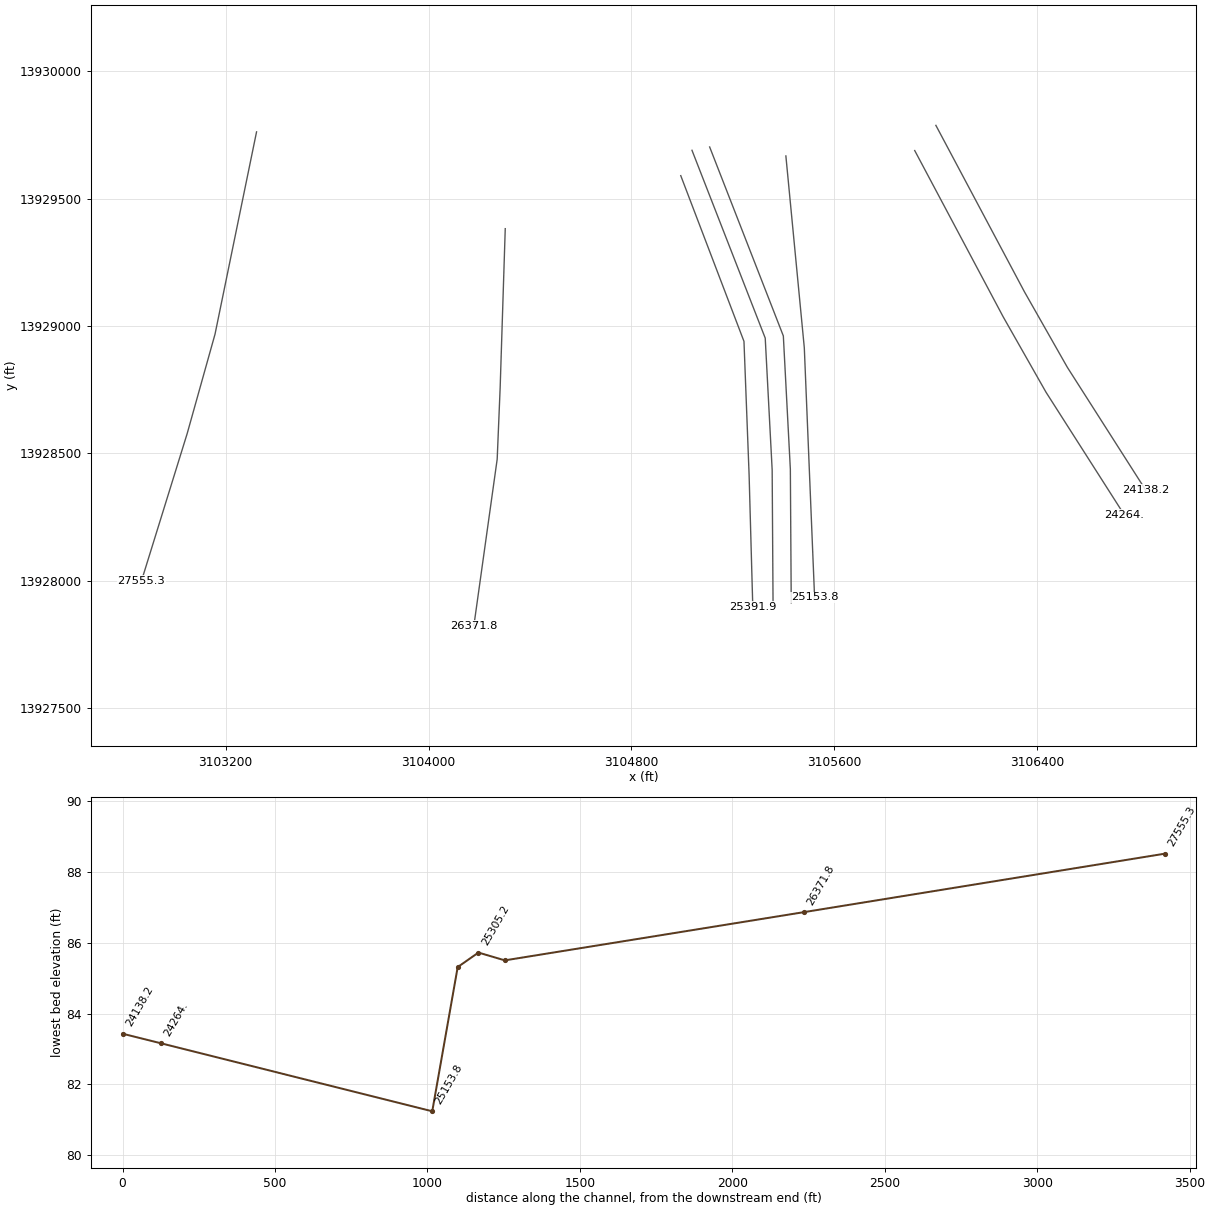
HEC-RAS study K111-00-00.prj: K111-00-00

--- K111-00-00.g02 (geometry) --- (continued)

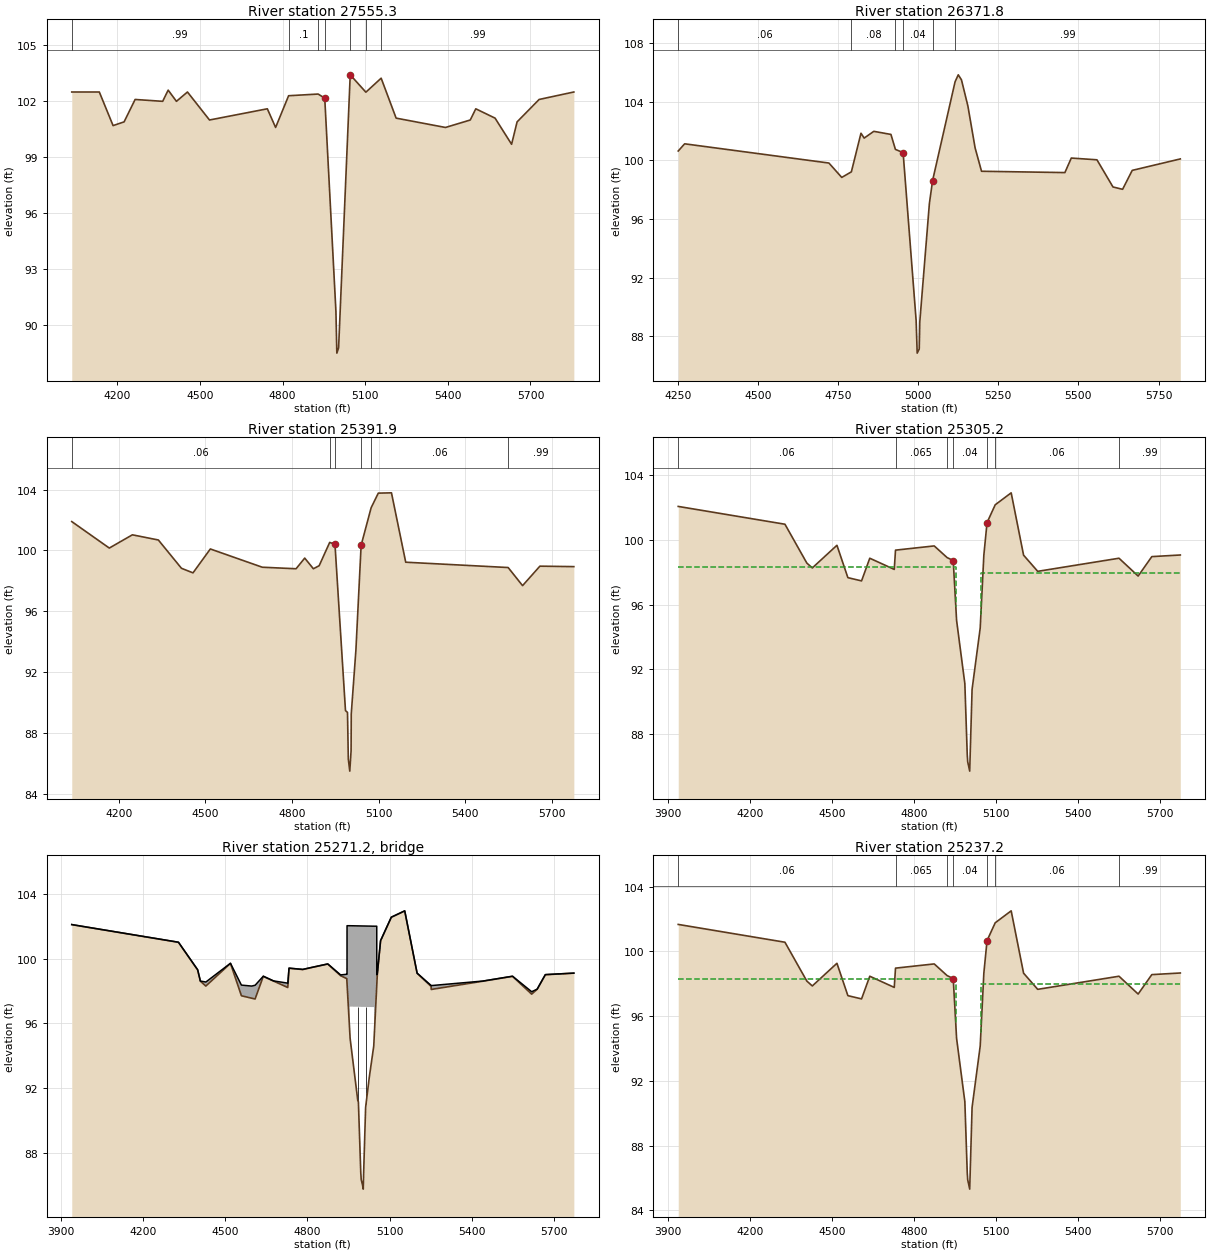
Type RM Length L Ch R = 1 ,27555.3 ,1167.1,1183.5,1194.1
BEGIN DESCRIPTION:
Cross Section K111-00-00-X14
END DESCRIPTION:
XS GIS Cut Line= 4
      3103322.09     13929762.38      3103158.32     13928967.55
      3103048.66     13928577.48      3102868.53     13927998.84
#Sta/Elev= 30
  4034.8   102.5  4134.8   102.5  4184.8   100.7  4224.8   100.9  4264.8   102.1
  4364.8     102  4384.8   102.6  4414.8     102  4454.8   102.5  4534.8     101
  4744.8   101.6  4774.8   100.6    4822   102.3  4929.2  102.39  4953.2  102.17
  4993.8   90.74  4997.1   88.51  5003.5   88.79  5045.7  103.42  5102.5  102.49
    5158  103.24  5212.3   101.1  5391.5   100.6  5481.5     101  5501.5   101.6
  5571.5   101.1  5631.5    99.7  5651.5   100.9  5731.5   102.1  5857.5   102.5
#Mann= 7 ,-1 , 0
  4034.8     .99       0    4822      .1       0  4929.2    .045       0
  4953.2     .04       0  5045.7    .045       0  5102.5     .06       0
    5158     .99       0
Bank Sta=4953.2,5045.7
Exp/Cntr=0.3,0.1

Type RM Length L Ch R = 1 ,26371.8 ,979,979.9,979.9
BEGIN DESCRIPTION:
Cross Section K111-00-00_X15c_int
END DESCRIPTION:
XS GIS Cut Line= 4
 3104302.477701713929382.1880219      3104282.45      13928759.2
       3104270.7      13928476.8      3104178.84      13927823.1
#Sta/Elev= 30
  4251.8  100.63  4271.8  101.12  4721.8   99.81  4761.8   98.83  4791.8   99.21
  4821.8  101.84  4831.8  101.51  4861.8  101.97  4915.2  101.76  4929.2  100.74
  4953.2  100.52  4993.8   89.09  4997.1   86.86  5003.5   87.14  5005.2   88.98
  5035.2   97.06  5045.2   98.62  5115.2  105.34  5125.2  105.82  5135.2  105.48
  5155.2   103.7  5177.8  100.84  5197.8   99.25  5457.8   99.16  5477.8  100.15
  5557.8  100.03  5607.8   98.18  5637.8   98.02  5667.8   99.31  5817.8  100.09
#Mann= 6 ,-1 , 0
  4251.8     .06       0  4791.8     .08       0  4929.2    .045       0
  4953.2     .04       0  5045.2    .045       0  5115.2     .99       0
Bank Sta=4953.2,5045.2
Exp/Cntr=0.3,0.1

Type RM Length L Ch R = 1 ,25391.9 ,86.7,86.7,86
BEGIN DESCRIPTION:
Cross Section K111-00-00-X15b
END DESCRIPTION:
XS GIS Cut Line= 4
      3104994.35      13929590.4      3105243.53     13928939.46
      3105263.76     13928415.16      3105278.26     13927897.79
#Sta/Elev= 30
  4037.2   101.9  4167.2  100.16  4247.2  101.03  4337.2  100.69  4417.2   98.83
  4457.2   98.53  4517.2   100.1  4697.2    98.9  4814.2    98.8  4844.2    99.5
  4874.2    98.8  4894.2      99  4930.7  100.53    4949  100.41  4985.4   89.48
  4992.4   89.36  4995.2    86.3  5000.3    85.5  5004.8   86.84  5005.4   89.26
  5021.5   93.45  5039.6  100.34  5074.3  102.81  5099.1  103.77  5144.7  103.79
  5194.1   99.23  5548.9   98.88  5598.9   97.69  5658.9   98.97  5776.5   98.94
#Mann= 6 ,-1 , 0
  4037.2     .06       0  4930.7    .045       0    4949     .04       0
  5039.6    .045       0  5074.3     .06       0  5548.9     .99       0
Bank Sta=4949,5039.6
Exp/Cntr=0.5,0.3

Type RM Length L Ch R = 1 ,25305.2 ,68,68,68
BEGIN DESCRIPTION:
Upstream Section of Bridge/Culvert/Weir
END DESCRIPTION:
XS GIS Cut Line= 4
      3105038.63     13929689.98      3105327.32      13928952.3
      3105354.67     13928434.36      3105358.17     13927910.32
#Sta/Elev= 30
  3938.6  102.07  4328.6  100.97  4408.6   98.57  4428.6   98.27  4518.6   99.67
  4558.6   97.67  4608.6   97.47  4638.6   98.87  4728.1   98.18 4732.66   99.37
  4874.2   99.63  4921.2   98.91  4943.6   98.73  4955.9   95.03  4986.1   91.12
  4994.8   86.74  4996.5    86.3  5003.8   85.72  5012.5   90.77  5042.2   94.56
  5055.5   99.06  5067.2  101.07    5097  102.17  5155.4  102.91  5200.7   99.06
  5252.3   98.06  5549.4   98.87  5619.4   97.77  5669.4   98.97  5773.5   99.07
#Mann= 7 ,-1 , 0
  3938.6     .06       0 4732.66    .065       0  4921.2    .045       0
  4943.6     .04       0  5067.2    .045       0    5097     .06       0
  5549.4     .99       0
#XS Ineff= 2 , 0
       0  4953.1    98.3  5044.5       0   97.95
Permanent Ineff=
       F       F
Bank Sta=4943.6,5067.2
Exp/Cntr=0.5,0.3

Type RM Length L Ch R = 3 ,25271.2 ,,,
BEGIN DESCRIPTION:
IMPERIAL VALLEY DRIVE
Structure ID: K111-00-00-S15
END DESCRIPTION:
Bridge Culvert--1,0,-1,-1, 0
Deck Dist Width WeirC Skew NumUp NumDn MinLoCord MaxHiCord MaxSubmerge Is_Ogee
10,48,2.6,0, 38, 39, , , 0.95, 0, ,,,
  3938.6  4328.6  4398.6  4408.6  4428.6  4518.6  4558.6  4595.9  4608.6  4638.6
  4675.9  4728.1  4732.6  4782.4  4874.2  4921.2  4943.6 4944.49  4944.6 4953.91
    4954 5043.79  5043.9  5053.2 5053.31  5055.5  5067.2  5106.4  5155.4  5200.7
  5251.7  5252.3  5440.9  5549.4  5619.4  5639.4  5669.4  5773.5
   102.1  101.01   99.31   98.61   98.55   99.71   98.36    98.3   98.35   98.91
   98.62   98.48   99.41   99.33   99.67   98.99   99.03   99.03  102.03  102.03
  102.03     102     102     102      99    99.1  101.11  102.56  102.95    99.1
   98.34   98.33   98.61   98.91   97.95   98.11   99.01    99.1
   102.1     101    99.3    98.6    98.3    99.7    97.7   97.55    97.5    98.9
   98.61   98.21    99.4   99.32   99.66   98.94   98.76   98.49   98.46   95.66
   97.03      97   95.17   98.31   98.35   99.09   101.1  102.55  102.94   99.09
   98.28   98.09    98.6    98.9    97.8    98.1      99    99.1
  3938.6  4328.6  4398.6  4408.6  4428.6  4518.6  4558.6  4595.9  4608.6  4638.6
  4675.9  4705.9  4728.1  4732.6  4782.4  4874.2  4921.2  4943.6 4944.49  4944.6
 4953.91    4954 5043.79  5043.9  5053.2 5053.31  5055.5  5067.2  5106.4  5155.4
  5200.7  5251.7  5252.3  5440.9  5549.4  5619.4  5639.4  5669.4  5773.5
  102.14  101.04   99.34   98.64   98.55   99.74   98.36    98.3   98.35   98.94
   98.65    98.5   98.48   99.44   99.36    99.7   98.99   99.03   99.03  102.03
  102.03  102.03     102     102     102      99   99.13  101.14  102.59  102.98
   99.13   98.34   98.33   98.64   98.94   97.95   98.14   99.04   99.14
  102.14  101.04   99.34   98.64   98.34   99.74   97.74   97.59   97.54   98.94
   98.65   98.42   98.25   99.44   99.36    99.7   98.98    98.8   98.53    98.5
    95.7   97.07   97.04   95.21   98.35   98.39   99.13  101.14  102.59  102.98
   99.13   98.32   98.13   98.64   98.94   97.84   98.14   99.04   99.14
Pier Skew, UpSta & Num, DnSta & Num=  ,4984, 2 ,4984, 2 , 0 , 0 , 0 ,,
     1.4     1.4
   90.19   98.02
     1.4     1.4
   90.23   98.06
Pier Skew, UpSta & Num, DnSta & Num=  ,5013.8, 2 ,5013.8, 2 , 0 , 0 , 0 ,,
     1.4     1.4
   89.88   98.01
     1.4     1.4
   89.92   98.05
BR Coef= 1 , 1 , 1 ,1.05, 0 ,,,0.8,0,1.2,0,
WSPro=,,,, 1 ,,,, 0 ,,,, 0 ,,,,-1 ,-1 ,-1 , 0 , 0 , 0 , 0 , 0
BR U #Sta/Elev= 67
  3938.6   102.1  3965.9  102.02  4315.9  101.04  4325.9  101.01  4328.6     101
  4398.6    99.3  4408.6    98.6  4428.6    98.3  4518.6    99.7  4558.6    97.7
  4595.9   97.55  4608.6    97.5  4638.6    98.9  4645.9   98.84  4675.9   98.61
  4705.9   98.38  4728.1   98.21  4732.6    99.4 4732.66    99.4  4778.3   99.33
  4782.4   99.32  4829.2    99.5  4832.4   99.51  4874.2   99.66  4887.8   99.45
  4921.2   98.94  4943.6   98.76 4944.49   98.49  4944.6   98.46 4944.71   98.43
 4953.91   95.66    4954   95.63  4954.1    95.6  4955.9   95.06    4984   91.21
  4986.1   91.15  4994.8   86.77  4996.5   86.33  5001.2   86.01  5003.8   85.75
  5005.3   86.76  5012.5    90.8  5025.9   92.66  5042.2   94.59  5043.7    95.1
 5043.79   95.13  5043.9   95.17 5053.09   98.27  5053.2   98.31 5053.31   98.35
  5055.5   99.09  5067.2   101.1    5097   102.2  5106.4  102.55  5148.9  102.89
  5155.4  102.94  5199.1   99.23  5200.7   99.09  5251.7   98.28  5252.3   98.09
  5440.9    98.6  5549.4    98.9  5619.4    97.8  5639.4    98.1  5669.4      99
  5764.5   99.09  5773.5    99.1
BR U #Mann= 7
  3938.6     .99 4732.66    .065  4921.2    .045  4943.6     .04  5067.2    .045
    5097     .06  5549.4     .99
BR U Banks=4943.6,5067.2
BR D #Sta/Elev= 67
  3938.6  102.14  3965.9  102.06  4315.9  101.08  4325.9  101.05  4328.6  101.04
  4398.6   99.34  4408.6   98.64  4428.6   98.34  4518.6   99.74  4558.6   97.74
  4595.9   97.59  4608.6   97.54  4638.6   98.94  4645.9   98.88  4675.9   98.65
  4705.9   98.42  4728.1   98.25  4732.6   99.44 4732.66   99.44  4778.3   99.37
  4782.4   99.36  4829.2   99.54  4832.4   99.55  4874.2    99.7  4887.8   99.49
  4921.2   98.98  4943.6    98.8 4944.49   98.53  4944.6    98.5 4944.71   98.47
 4953.91    95.7    4954   95.67  4954.1   95.64  4955.9    95.1    4984   91.25
  4986.1   91.19  4994.8   86.81  4996.5   86.37  5001.2   86.05  5003.8   85.79
  5005.3    86.8  5012.5   90.84  5025.9    92.7  5042.2   94.63  5043.7   95.14
 5043.79   95.17  5043.9   95.21 5053.09   98.31  5053.2   98.35 5053.31   98.39
  5055.5   99.13  5067.2  101.14    5097  102.24  5106.4  102.59  5148.9  102.93
  5155.4  102.98  5199.1   99.27  5200.7   99.13  5251.7   98.32  5252.3   98.13
  5440.9   98.64  5549.4   98.94  5619.4   97.84  5639.4   98.14  5669.4   99.04
  5764.5   99.13  5773.5   99.14
BR D #Mann= 7
  3938.6     .99 4732.66    .065  4921.2    .045  4943.6     .04  5067.2    .045
    5097     .06  5549.4     .99
BR D Banks=4943.6,5067.2
BC Design=,, 0 ,, 0 ,,,,,,
BC HTab HWMax=102.91

Type RM Length L Ch R = 1 ,25237.2 ,83,83.4,83.4
BEGIN DESCRIPTION:
Downstream Section of Bridge/Culvert/Weir
END DESCRIPTION:
XS GIS Cut Line= 4
      3105108.25     13929703.03      3105398.71     13928960.83
      3105426.36     13928437.36      3105429.86     13927912.63
#Sta/Elev= 30
  3938.6  101.66  4328.6  100.56  4408.6   98.16  4428.6   97.86  4518.6   99.26
  4558.6   97.26  4608.6   97.06  4638.6   98.46  4728.1   97.77 4732.66   98.96
  4874.2   99.22  4921.2    98.5  4943.6   98.32  4955.9   94.62  4986.1   90.71
  4994.8   86.33  4996.5   85.89  5003.8   85.31  5012.5   90.36  5042.2   94.15
  5055.5   98.65  5067.2  100.66    5097  101.76  5155.4   102.5  5200.7   98.65
  5252.3   97.65  5549.4   98.46  5619.4   97.36  5669.4   98.56  5773.5   98.66
#Mann= 7 ,-1 , 0
  3938.6     .06       0 4732.66    .065       0  4921.2    .045       0
  4943.6     .04       0  5067.2    .045       0    5097     .06       0
  5549.4     .99       0
#XS Ineff= 2 , 0
       0  4953.1    98.3  5044.5       0   97.95
Permanent Ineff=
       F       F
Bank Sta=4943.6,5067.2
Exp/Cntr=0.5,0.3

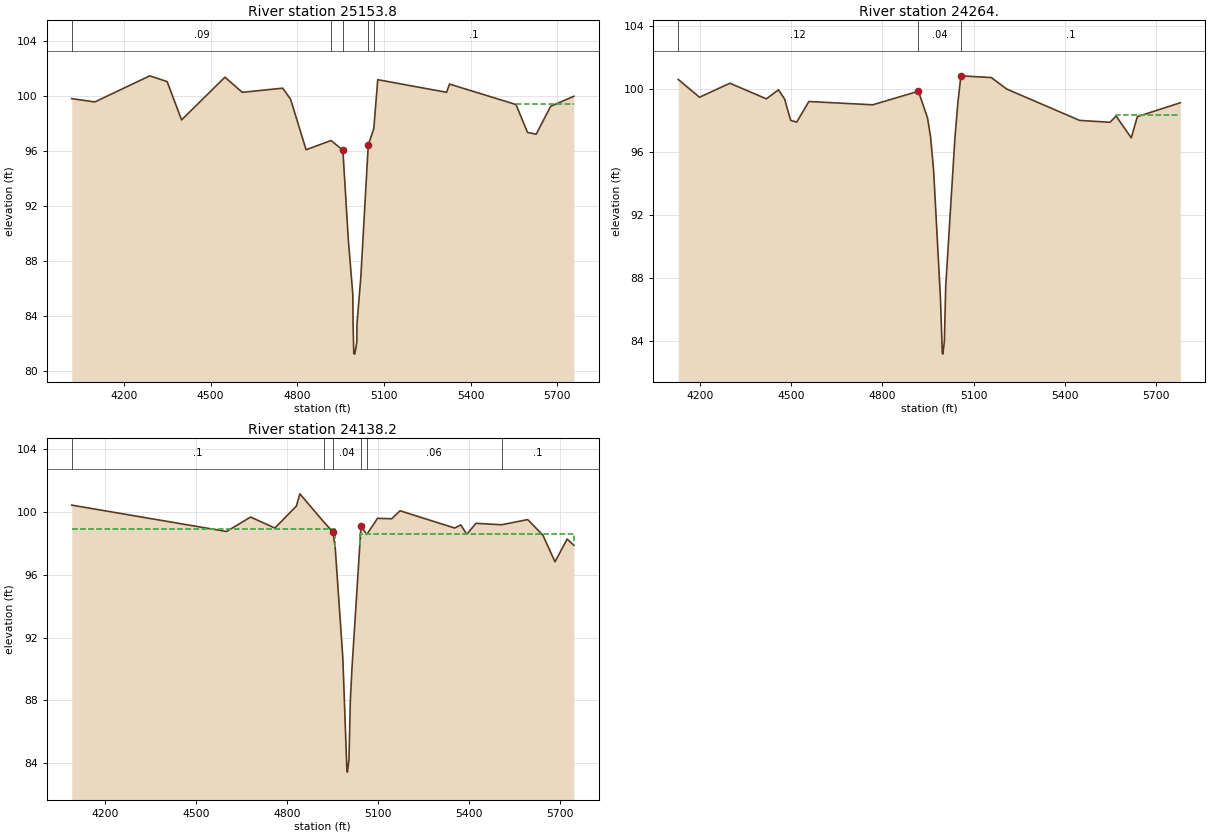
Type RM Length L Ch R = 1 ,25153.8 ,872.1,889.8,911.2
BEGIN DESCRIPTION:
Cross Section K111-00-00-X15a
END DESCRIPTION:
XS GIS Cut Line= 3
      3105408.71      13929667.8      3105481.38     13928914.28
      3105521.87     13927934.82
#Sta/Elev= 30
  4019.8   99.84  4099.8    99.6  4289.8   101.5  4349.8  101.08  4399.8   98.29
  4549.8   101.4  4609.8   100.3  4749.8   100.6  4776.9    99.8  4830.7   96.12
  4916.9   96.79  4957.9   96.09  4976.6   89.63  4992.3    85.6  4993.3   83.44
  4995.7   81.28  4999.1   81.24  5006.2   82.11  5006.8   83.47    5020   86.83
  5045.8   96.47  5064.9   97.64  5078.6  101.22  5316.9   100.3  5326.9   100.9
  5556.9   99.41  5596.9   97.38  5626.9   97.25  5676.9   99.28  5757.2  100.01
#Mann= 5 ,-1 , 0
  4019.8     .09       0  4916.9    .045       0  4957.9     .04       0
  5045.8    .045       0  5064.9      .1       0
#XS Ineff= 2 , 0
                         5555.77           99.42
Permanent Ineff=
       F       F
Bank Sta=4957.9,5045.8
Exp/Cntr=0.3,0.1

Type RM Length L Ch R = 1 ,24264.  ,124,125.8,129
BEGIN DESCRIPTION:
K111-00-00-S14 - PL DS - XS 4
END DESCRIPTION:
XS GIS Cut Line= 4
      3105916.63     13929688.96       3106265.4     13929035.79
      3106434.08     13928739.95      3106742.26     13928258.84
#Sta/Elev= 30
  4128.2   100.6  4198.2   99.47  4298.2  100.36  4418.2   99.37  4458.2   99.94
  4478.2   99.36  4498.2      98  4518.2   97.89  4558.2    99.2  4768.2   98.99
  4918.6   99.85  4948.6   98.16  4958.6   96.96  4968.6   94.85 4991.21   86.71
  4997.3   83.22 4998.97   83.16  5004.1   83.96 5008.52   87.46  5038.6   96.82
  5048.6   99.14  5058.6  100.83  5158.6  100.72  5209.2   99.99  5449.2      98
  5549.2   97.88  5569.2   98.28  5619.2   96.89  5639.2   98.24  5780.6   99.12
#Mann= 3 ,-1 , 0
  4128.2     .12       0  4918.6     .04       0  5058.6      .1       0
#XS Ineff= 2 , 0
                         5568.46           98.32
Permanent Ineff=
       F       F
Bank Sta=4918.6,5058.6
Exp/Cntr=0.5,0.3

Type RM Length L Ch R = 1 ,24138.2 ,21,21,21
BEGIN DESCRIPTION:
Upstream Section of Bridge/Culvert/Weir
END DESCRIPTION:
XS GIS Cut Line= 4
      3106000.05      13929787.9      3106349.01     13929134.44
      3106518.29     13928837.56      3106826.88      13928355.7
#Sta/Elev= 30
  4090.4  100.44  4600.4   98.76  4679.8   99.68  4759.8   98.98  4830.7  100.38
 4842.15  101.16 4920.05   99.39 4951.15   98.72 4958.65   97.73 4983.75    90.7
 4997.25    83.5 4998.95   83.43 5004.05   84.25 5008.45   87.94 5013.65   89.98
 5043.65   99.09 5062.75   98.57 5098.15    99.6 5144.65   99.57  5172.4  100.08
  5352.4   98.98  5372.4   99.18  5392.4   98.58  5422.4   99.28  5507.3   99.19
    5593   99.52    5643   98.53    5683   96.83    5723   98.28  5745.1   97.88
#Mann= 6 ,-1 , 0
  4090.4      .1       0 4920.05    .045       0 4951.15     .04       0
 5043.65    .045       0 5062.75     .06       0  5507.3      .1       0
#XS Ineff= 2 , 0
       0 4958.25   98.93 5039.72       0   98.59
Permanent Ineff=
       F       F
Bank Sta=4951.15,5043.65
Exp/Cntr=0.5,0.3