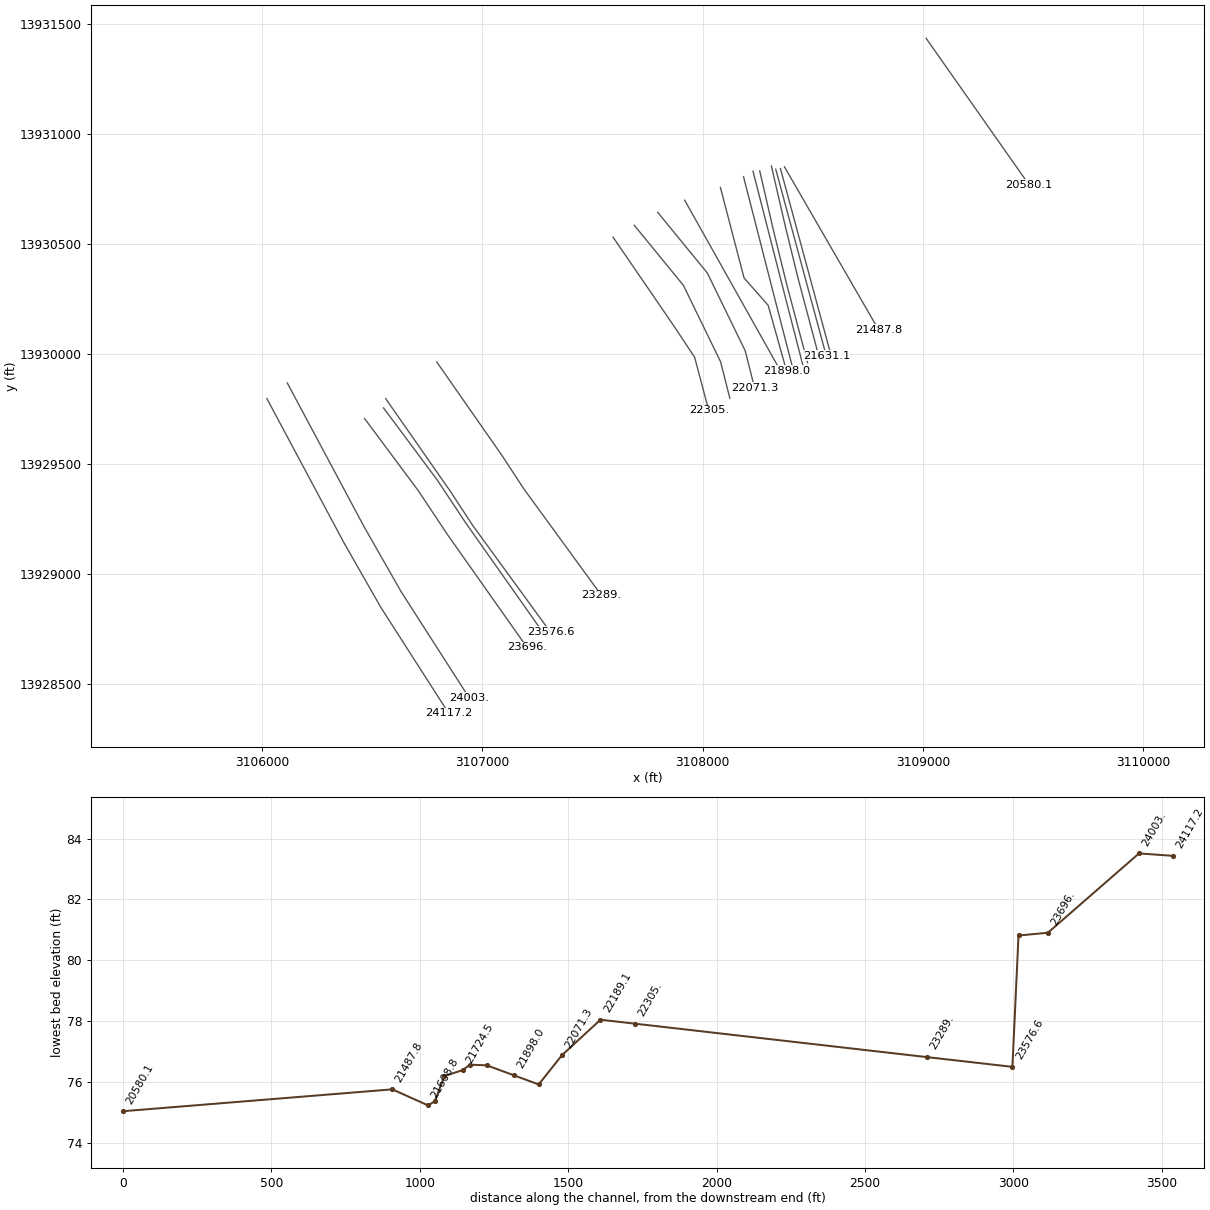
HEC-RAS study K111-00-00.prj: K111-00-00

--- K111-00-00.g02 (geometry) --- (continued)

Type RM Length L Ch R = 3 ,24127.7 ,,,
BEGIN DESCRIPTION:
PL1_K111-00-00-S14
END DESCRIPTION:
Bridge Culvert--1,0,-1,-1, 0
Deck Dist Width WeirC Skew NumUp NumDn MinLoCord MaxHiCord MaxSubmerge Is_Ogee
10,1,2.6,0, 21, 21, , , 0.95, 0, ,,,
 4920.05 4949.15 4949.26 4949.35 4951.15 4958.65 4983.75 4986.55 4995.95 4997.25
 4998.95 5002.85 5004.05 5008.45 5013.65 5028.35 5039.64 5039.75 5043.65 5049.05
 5062.75
   99.41   98.93   98.93   98.93   98.93   98.95      99      99   99.02   99.02
   99.02   99.03   99.03   99.04   99.05   99.08    99.1    99.1   99.11   99.12
   98.59
                                           97.75   97.67   97.67   97.69   97.69
   97.69    97.7    97.7   97.71   97.72   97.75   97.85
        
 4920.05 4949.15 4949.26 4949.35 4951.15 4958.65 4983.75 4986.55 4995.95 4997.25
 4998.95 5002.85 5004.05 5008.45 5013.65 5028.35 5039.64 5039.75 5043.65 5049.05
 5062.75
   99.41   98.93   98.93   98.93   98.93   98.95      99      99   99.02   99.02
   99.02   99.03   99.03   99.04   99.05   99.08    99.1    99.1   99.11   99.12
   98.59
                                           97.75   97.67   97.67   97.69   97.69
   97.69    97.7    97.7   97.71   97.72   97.75   97.85
        
Pier Skew, UpSta & Num, DnSta & Num=  ,4983.8, 2 ,4983.8, 2 , 0 , 0 , 0 ,,
     1.2     1.2
    89.4   98.67
     1.2     1.2
    89.4   98.67
Pier Skew, UpSta & Num, DnSta & Num=  ,5013.7, 2 ,5013.7, 2 , 0 , 0 , 0 ,,
     1.2     1.2
   88.76   98.72
     1.2     1.2
   88.76   98.72
BR Coef= 1 , 1 , 1 ,0.9, 0 ,,,0.8,0,1.2,0,
WSPro=,,,, 1 ,,,, 0 ,,,, 0 ,,,,-1 ,-1 ,-1 , 0 , 0 , 0 , 0 , 0
BC Design=,, 0 ,, 0 ,,,,,,
BC HTab HWMax=101.16

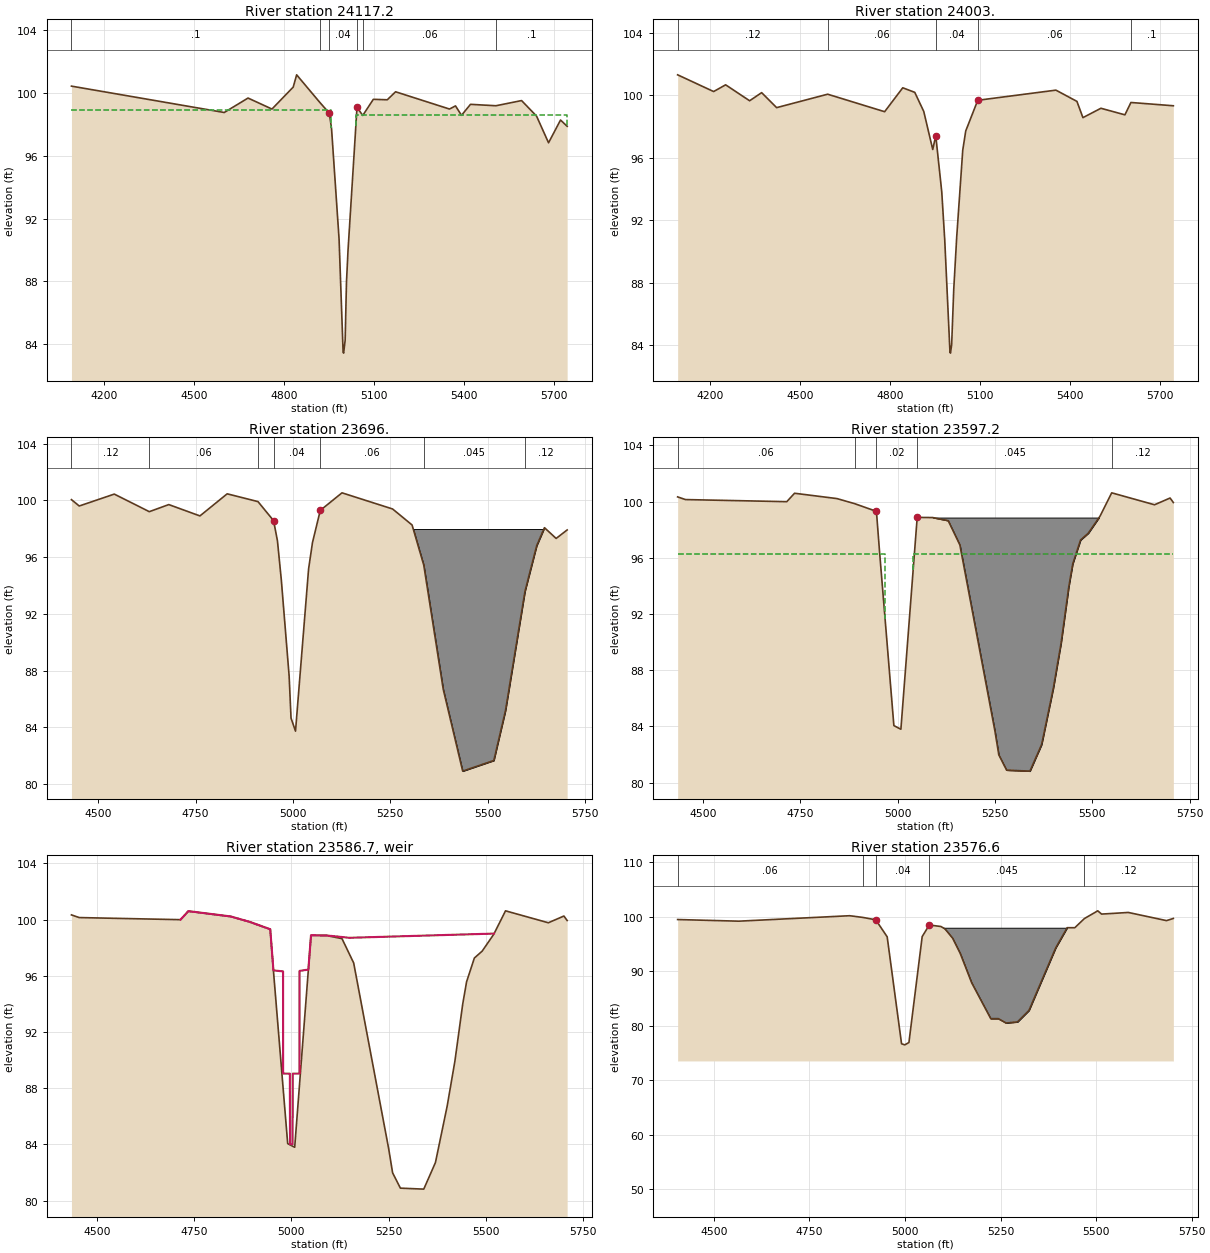
Type RM Length L Ch R = 1 ,24117.2 ,114,114.2,114.2
BEGIN DESCRIPTION:
Downstream Section of Bridge/Culvert/Weir
END DESCRIPTION:
XS GIS Cut Line= 4
      3106021.99      13929798.3      3106370.76     13929145.17
      3106539.44     13928849.33      3106847.62      13928368.2
#Sta/Elev= 30
  4090.4  100.44  4600.4   98.76  4679.8   99.68  4759.8   98.98  4830.7  100.38
 4842.15  101.16 4920.05   99.39 4951.15   98.72 4958.65   97.73 4983.75    90.7
 4997.25    83.5 4998.95   83.43 5004.05   84.25 5008.45   87.94 5013.65   89.98
 5043.65   99.09 5062.75   98.57 5098.15    99.6 5144.65   99.57  5172.4  100.08
  5352.4   98.98  5372.4   99.18  5392.4   98.58  5422.4   99.28  5507.3   99.19
    5593   99.52    5643   98.53    5683   96.83    5723   98.28  5745.1   97.88
#Mann= 6 ,-1 , 0
  4090.4      .1       0 4920.05    .045       0 4951.15     .04       0
 5043.65    .045       0 5062.75     .06       0  5507.3      .1       0
#XS Ineff= 2 , 0
       0 4958.25   98.93 5039.72       0   98.59
Permanent Ineff=
       F       F
Bank Sta=4951.15,5043.65
Exp/Cntr=0.5,0.3

Type RM Length L Ch R = 1 ,24003.  ,302,307,307
BEGIN DESCRIPTION:
K111-00-00-S14 - PL DS - XS 1
END DESCRIPTION:
XS GIS Cut Line= 4
       3106114.7     13929868.66      3106463.47      13929215.5
      3106632.15     13928919.66      3106940.33     13928438.54
#Sta/Elev= 30
  4091.4  101.32  4211.4  100.25  4251.4  100.68  4331.4   99.66  4371.4  100.18
  4421.4   99.22  4591.4  100.08  4781.4   98.96  4841.8  100.49  4881.8   100.2
  4911.8   98.98  4941.8   96.54  4951.8   97.43  4971.8   93.84  4981.8   90.74
 4999.23   83.57 5001.05   83.51 5004.89   84.08  5011.8    87.6  5021.8   90.98
  5041.8    96.5  5051.8   97.73  5091.8   99.69  5352.4  100.34  5422.4   99.62
  5442.4   98.58  5502.4   99.18  5582.4   98.76  5602.4   99.55  5743.8   99.34
#Mann= 5 ,-1 , 0
  4091.4     .12       0  4591.4     .06       0  4951.8     .04       0
  5091.8     .06       0  5602.4      .1       0
Bank Sta=4951.8,5091.8
Exp/Cntr=0.3,0.1

Type RM Length L Ch R = 1 ,23696.  ,97,98.8,98.8
BEGIN DESCRIPTION:
K111-00-00-S13 US_FIELD - DAM - XS 4
END DESCRIPTION:
XS GIS Cut Line= 4
      3106465.28     13929707.39      3106709.53     13929379.23
      3106839.92     13929182.72      3107201.81     13928669.17
#Sta/Elev= 30
  4431.2  100.06  4451.2   99.61  4541.2  100.45  4631.2   99.21  4681.2   99.71
  4761.2   98.91  4831.2  100.47  4910.3   99.92  4950.3   98.58  4960.3   97.16
  4970.3   94.38  4990.3   87.62 4995.22   84.64 5006.69   83.72  5040.3   95.17
  5050.3   97.03  5070.3    99.3  5126.1  100.54  5256.1    99.4  5306.1   98.27
  5336.1   95.44  5386.1   86.68  5436.1    80.9  5516.1   81.65  5546.1   85.18
  5596.1   93.59  5626.1    96.8  5646.1   98.08  5676.1   97.32  5704.4   97.92
#Mann= 7 ,-1 , 0
  4431.2     .12       0  4631.2     .06       0  4910.3    .045       0
  4950.3     .04       0  5070.3     .06       0  5336.1    .045       0
  5596.1     .12       0
#Block Obstruct= 1 ,-1
 5302.48 5647.02   97.99
Bank Sta=4950.3,5070.3
Exp/Cntr=0.7,0.5

Type RM Length L Ch R = 1 ,23597.2 ,20.6,20.6,20.6
BEGIN DESCRIPTION:
Upstream Section of Bridge/Culvert/Weir
END DESCRIPTION:
XS GIS Cut Line= 4
      3106551.59      13929755.3      3106795.85     13929427.18
      3106926.24     13929230.68      3107288.13     13928717.12
#Sta/Elev= 30
  4435.1  100.33  4455.1  100.14  4715.4   99.99  4735.4  100.59  4844.3  100.21
  4889.6   99.85  4945.7    99.3  4953.9   96.36  4990.5   84.05  5008.5   83.79
  5050.4   98.87    5090   98.86    5130   98.64    5160   96.91    5250   83.67
    5260   81.97    5280   80.88    5340   80.81    5370    82.7    5400    86.7
    5420   89.92    5440   93.97    5450   95.57    5470   97.26    5490   97.75
    5520   98.96    5550  100.62    5660   99.77    5700  100.25  5708.3   99.93
#Mann= 5 ,-1 , 0
  4435.1     .06       0  4889.6    .045       0  4945.7     .02       0
  5050.4    .045       0    5550     .12       0
#XS Ineff= 2 , 0
       0    4968    96.3    5040       0    96.3
Permanent Ineff=
       F       F
#Block Obstruct= 1 ,-1
    5090    5600   98.86
Bank Sta=4945.7,5050.4
Exp/Cntr=0.7,0.5

Type RM Length L Ch R = 5 ,23586.7 ,,,
BEGIN DESCRIPTION:
1000' US HARDY TOLL ROAD; minor trib on right flowing into K111-00-bracketed out pts VRR
Structure ID: K111-00-00-S13
END DESCRIPTION:
IW Pilot Flow=0
#Inline Weir SE= 19
  4715.4     100  4735.4   100.6  4844.3  100.22  4895.1   99.82  4945.7   99.31
  4953.9   96.38  4978.6   96.31 4978.71   89.03  4996.1   89.03  4996.5      84
  5003.2      84  5003.5   89.03  5020.7   89.03  5020.8   96.34  5043.6   96.44
  5050.4   98.88    5090   98.87  5148.7    98.7  5520.3      99
IW Dist,WD,Coef,Skew,MaxSub,Min_El,Is_Ogee,SpillHt,DesHd
10,1,3,0,0.95,, 0 ,,,0,0,

Type RM Length L Ch R = 1 ,23576.6 ,287.6,287.6,276.3
BEGIN DESCRIPTION:
Cross Section FIELD_DS;
minor trib on right flowing into K111-00
Located At: 1000' US HARDY TOLL ROAD
END DESCRIPTION:
XS GIS Cut Line= 4
      3106561.46     13929797.41      3106857.11     13929373.17
      3106956.89     13929220.74      3107308.86     13928737.51
#Sta/Elev= 30
    4405    99.5    4565    99.2    4855   100.2  4889.6   99.89  4923.4   99.45
  4953.3   96.33  4990.9   76.69  4999.3   76.49  5010.2   76.92  5044.9   96.37
  5063.5    98.5  5093.9   98.22  5104.3    97.8  5124.3    96.1  5144.3    93.3
  5174.3    87.9  5224.3    81.3  5244.3    81.3  5264.3    80.5  5294.3    80.7
  5324.3    82.8  5394.3    94.3  5424.3      98  5444.3      98  5469.4   99.68
  5504.3   101.1  5514.3   100.5  5584.3   100.8  5684.3    99.3  5702.1    99.7
#Mann= 5 ,-1 , 0
    4405     .06       0  4889.6    .045       0  4923.4     .04       0
  5063.5    .045       0  5469.4     .12       0
#Block Obstruct= 2 ,-1
    5093    5424      98    5425    5426      50
Bank Sta=4923.4,5063.5
Exp/Cntr=0.7,0.5

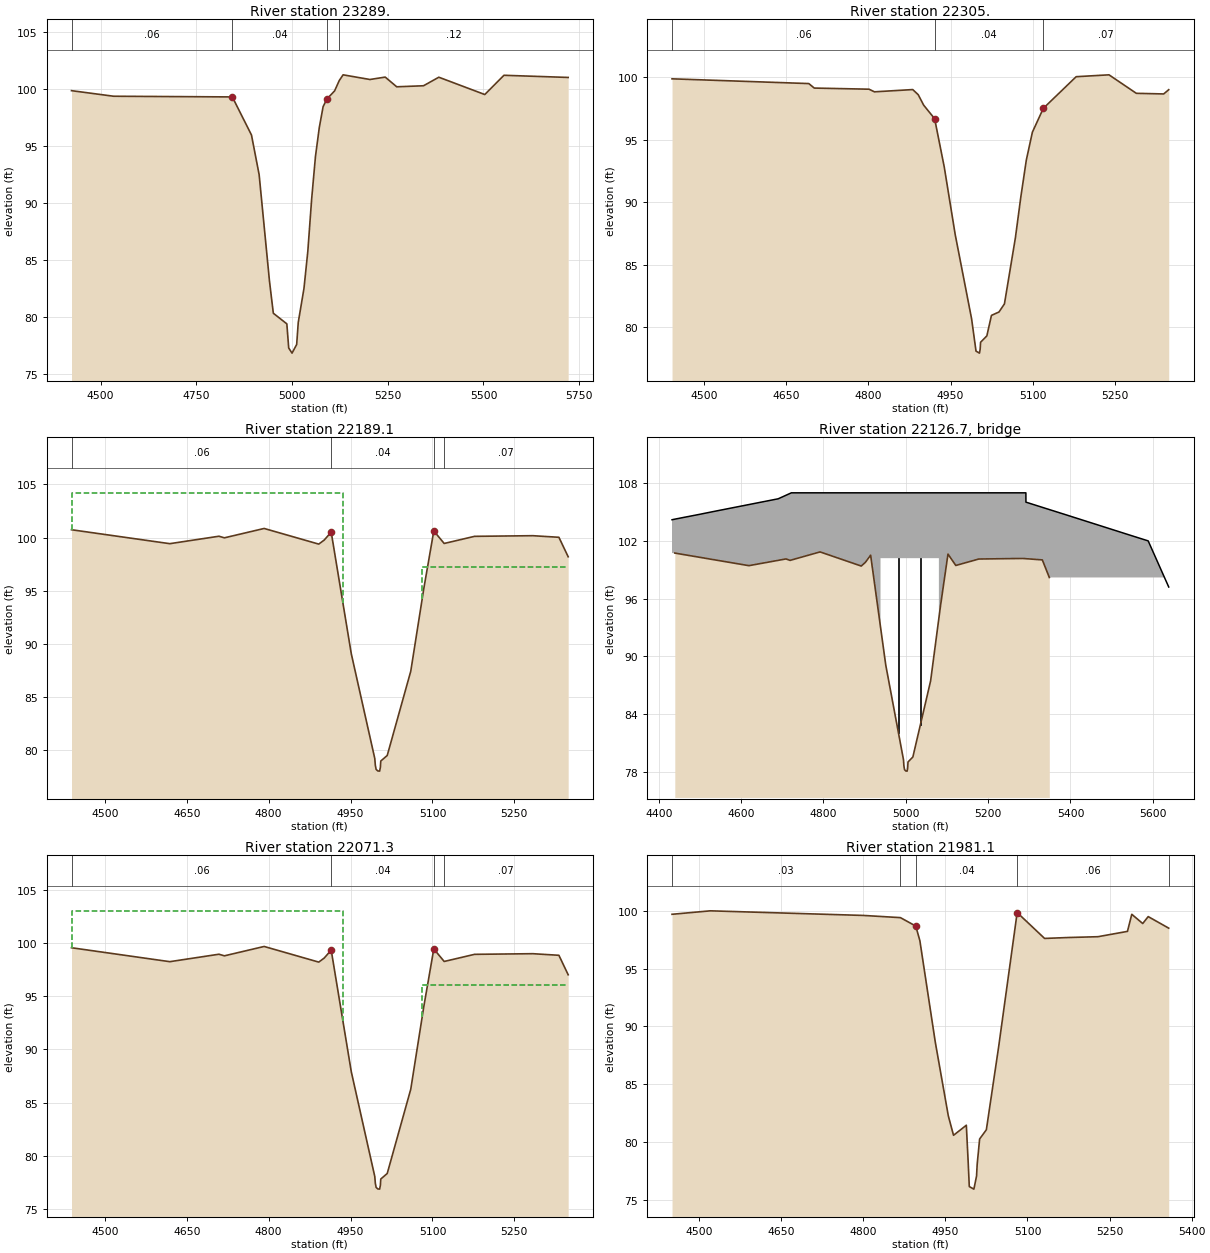
Type RM Length L Ch R = 1 ,23289.  ,984,984,945.4
BEGIN DESCRIPTION:
K111-00-00-S13 DS_FIELD - DAM - XS 1
END DESCRIPTION:
XS GIS Cut Line= 4
      3106793.24     13929963.81      3107088.88     13929539.58
      3107188.66     13929387.15      3107540.63     13928903.92
#Sta/Elev= 30
  4424.2   99.85  4534.2   99.36  4844.2    99.3  4894.2   95.96  4914.2   92.48
  4941.3   83.11  4951.3   80.31 4986.57   79.38 4991.44   77.26 5000.13   76.81
 5012.26   77.57 5016.38   79.51  5031.3   82.49  5041.3   85.73  5051.3   90.31
  5061.3   94.07  5071.3   96.61  5081.3   98.45  5091.3   99.12  5111.3   99.83
  5123.5  100.74  5133.5  101.24  5203.5  100.83  5243.5  101.04  5273.5  100.19
  5343.5  100.28  5383.5  101.03  5503.5   99.51  5553.5   101.2  5721.3  101.01
#Mann= 4 ,-1 , 0
  4424.2     .06       0  4844.2     .04       0  5091.3    .045       0
  5123.5     .12       0
Bank Sta=4844.2,5091.3
Exp/Cntr=0.3,0.1

Type RM Length L Ch R = 1 ,22305.  ,115.9,115.9,111.4
BEGIN DESCRIPTION:
K111-00-00-S12 TOPO - HARDY TOLL RD US - XS 4
END DESCRIPTION:
XS GIS Cut Line= 4
      3107593.33     13930530.51      3107868.74     13930128.14
      3107963.26      13929985.5       3108027.3     13929744.67
#Sta/Elev= 30
    4441   99.86    4691   99.48    4701   99.12    4801   99.03    4811   98.82
    4881      99    4891   98.59    4901   97.75    4921   96.67  4938.6    92.8
  4958.6    87.4  4988.6   80.65 4996.64   78.07 5002.97   77.91 5004.23   78.23
    5005   78.78 5016.45   79.29 5024.86   80.93  5038.6    81.2  5048.6   81.85
  5068.6   87.13  5078.6   90.42  5088.6   93.36  5099.7   95.59  5119.7    97.5
  5179.7  100.03  5239.7  100.18  5289.7    98.7  5339.7   98.65  5348.9   98.99
#Mann= 3 ,-1 , 0
    4441     .06       0    4921     .04       0  5119.7     .07       0
Bank Sta=4921,5119.7
Exp/Cntr=0.5,0.3

Type RM Length L Ch R = 1 ,22189.1 ,130.1,130.1,130.1
BEGIN DESCRIPTION:
Upstream Section of Bridge/Culvert/Weir
END DESCRIPTION:
XS GIS Cut Line= 4
      3107689.24     13930584.86      3107912.54     13930311.68
       3108081.2     13929964.85       3108123.2       13929799.
#Sta/Elev= 25
    4439  100.73    4619   99.42    4709  100.12    4719   99.97  4791.8  100.85
  4891.8   99.38  4901.8   99.76  4914.6  100.51  4951.4   89.07  4994.4   79.23
  4995.4    78.6  4996.9    78.2  4999.9   78.06  5003.3   78.04  5004.6   78.38
  5005.4   78.99  5017.2   79.51  5060.3   87.43  5084.3   95.23  5102.5  100.62
  5121.5   99.44  5177.2  100.11  5283.9  100.17  5331.6  100.02  5348.6   98.19
#Mann= 4 ,-1 , 0
    4439     .06       0  4914.6     .04       0  5102.5    .045       0
  5121.5     .07       0
#XS Ineff= 2 , 0
       0  4936.6   104.2 5081.29       0    97.2
Permanent Ineff=
       F       F
Bank Sta=4914.6,5102.5
Exp/Cntr=0.5,0.3

Type RM Length L Ch R = 3 ,22126.7 ,,,
BEGIN DESCRIPTION:
HARDY TOLL ROAD
Structure ID: K111-00-00-S12
END DESCRIPTION:
Bridge Culvert--1,0,-1,-1, 0
Deck Dist Width WeirC Skew NumUp NumDn MinLoCord MaxHiCord MaxSubmerge Is_Ogee
10,117.1,2.6,0, 18, 17, , , 0.95, 0, ,,,
  4432.3  4440.1  4500.1  4530.1  4690.1  4722.1  4938.6  4938.6 5080.39 5080.39
  5291.7 5291.81  5331.6  5348.6  5388.6  5548.6  5588.7  5638.6
   104.2  104.27  104.77  105.03  106.38     107     107     107     107     107
     107  106.03  105.49  105.26  104.72  102.54     102    97.2
                                                           100.2   100.2
                                                                
  4432.3  4440.1  4500.1  4530.1  4690.1  4722.1  4938.6  4938.6 5080.39 5080.39
  5291.7  5331.6  5348.6  5388.6  5548.6  5588.7  5638.6
   104.2  104.27  104.77  105.03  106.38     107     107     107     107     107
     107  105.49  105.26  104.72  102.54     102    97.2
                                                           100.2   100.2
                                                        
Pier Skew, UpSta & Num, DnSta & Num=  ,4982.4, 2 ,4982.4, 2 , 0 , 0 , 0 ,,
     1.5     1.5
   80.81     102
     1.5     1.5
   79.75     102
Pier Skew, UpSta & Num, DnSta & Num=  ,5035.2, 2 ,5035.2, 2 , 0 , 0 , 0 ,,
     1.5     1.5
   81.69     102
     1.5     1.5
   80.63     102
BR Coef= 1 , 1 , 1 ,1.05, 0 ,,,0.8,0,1.2,0,
WSPro=,,,, 1 ,,,, 0 ,,,, 0 ,,,,-1 ,-1 ,-1 , 0 , 0 , 0 , 0 , 0
BC Design=,, 0 ,, 0 ,,,,,,
BC HTab HWMax=100.85

Type RM Length L Ch R = 1 ,22071.3 ,77.7,77.9,77.9
BEGIN DESCRIPTION:
Downstream Section of Bridge/Culvert/Weir
END DESCRIPTION:
XS GIS Cut Line= 4
      3107795.69     13930643.65      3108021.21     13930367.75
      3108192.75       13930015.      3108235.51      13929846.1
#Sta/Elev= 25
    4439   99.56    4619   98.25    4709   98.95    4719    98.8  4791.8   99.68
  4891.8   98.21  4901.8   98.59  4914.6   99.34  4951.4    87.9  4994.4   78.06
  4995.4   77.43  4996.9   77.03  4999.9   76.89  5003.3   76.87  5004.6   77.21
  5005.4   77.82  5017.2   78.34  5060.3   86.26  5084.3   94.06  5102.5   99.45
  5121.5   98.27  5177.2   98.94  5283.9      99  5331.6   98.85  5348.6   97.02
#Mann= 4 ,-1 , 0
    4439     .06       0  4914.6     .04       0  5102.5    .045       0
  5121.5     .07       0
#XS Ineff= 2 , 0
       0  4936.6  103.03 5081.29       0   96.03
Permanent Ineff=
       F       F
Bank Sta=4914.6,5102.5
Exp/Cntr=0.5,0.3

Type RM Length L Ch R = 1 ,21981.1 ,64.8,83.1,100.2
BEGIN DESCRIPTION:
Cross Section K111-00-00-X12a; Parking Lot on left VRR
END DESCRIPTION:
XS GIS Cut Line= 2
      3107918.05     13930698.73       3108362.1     13929907.25
#Sta/Elev= 27
  4450.6    99.7  4520.6     100  4800.6    99.6  4867.9   99.41  4895.9   98.68
  4903.4   97.42  4931.6   88.63  4955.4   82.25  4964.9   80.57  4988.3   81.44
  4991.9   78.04  4993.7   76.13  5002.1   75.91    5007   77.05  5008.1   78.04
  5012.6   80.25  5024.9   81.05  5047.3   88.21  5081.2   99.85  5131.3   97.61
    5175   97.69  5228.8   97.76  5282.7   98.22  5290.6    99.7  5310.6    98.9
  5320.6    99.5  5358.1    98.5
#Mann= 5 ,-1 , 0
  4450.6     .03       0  4867.9    .045       0  4895.9     .04       0
  5081.2     .06       0  5358.1     .99       0
Bank Sta=4895.9,5081.2
Exp/Cntr=0.3,0.1

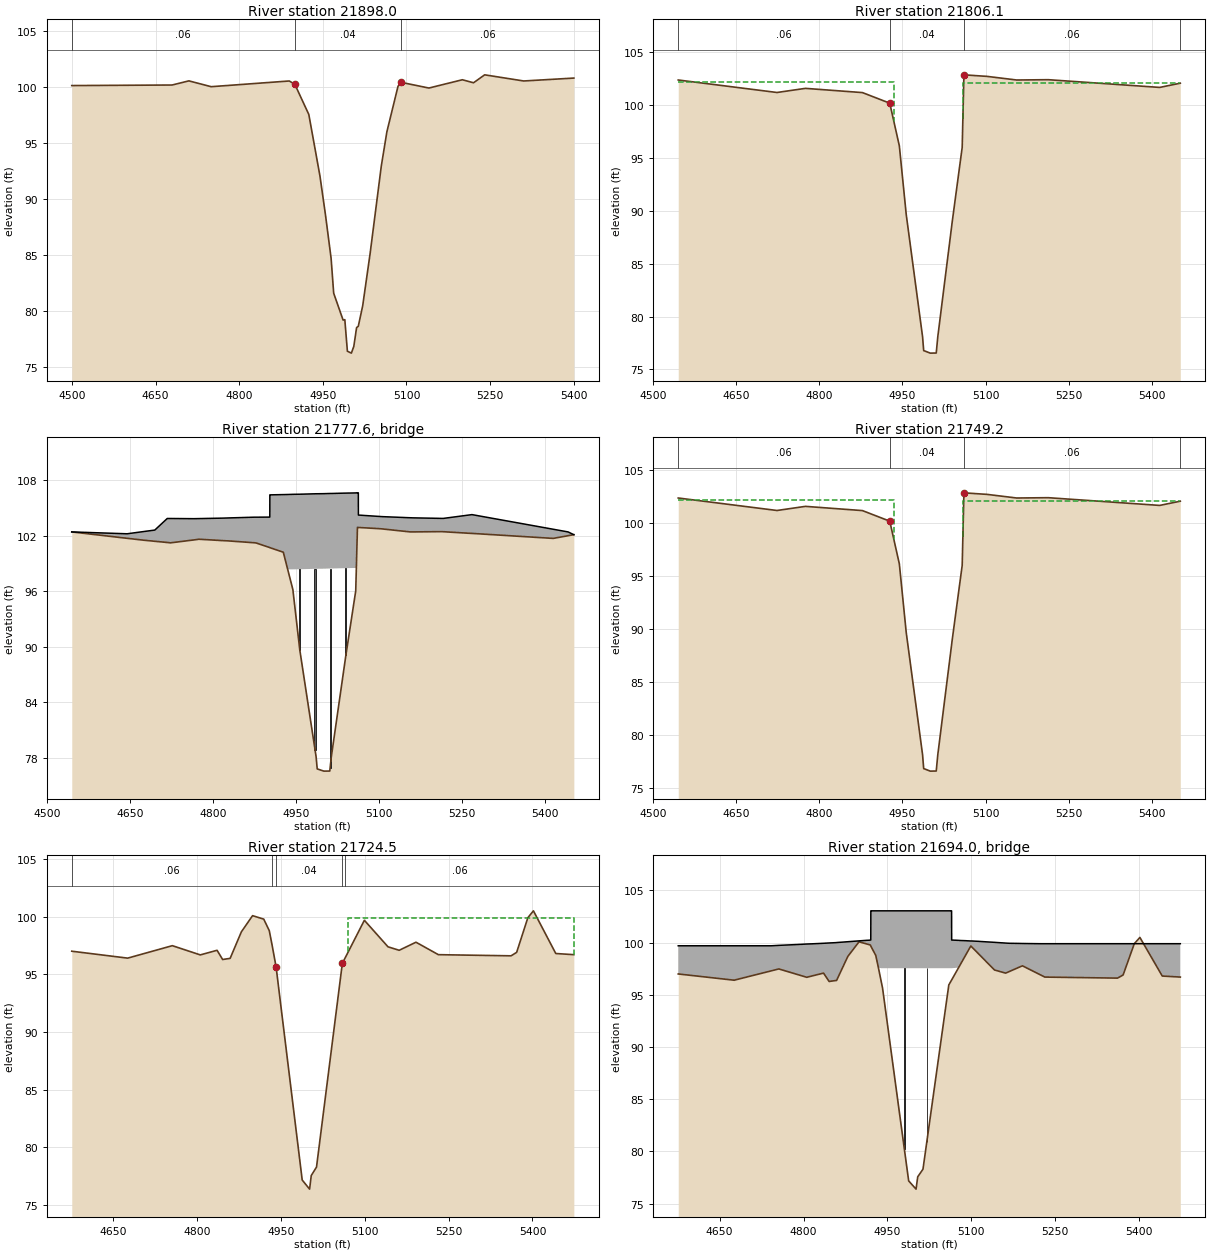
Type RM Length L Ch R = 1 ,21898.0 ,122.8,91.9,68.8
BEGIN DESCRIPTION:
K111-00-00-S11 TOPO UNION PACIFIC RR US - XS 4
END DESCRIPTION:
XS GIS Cut Line= 4
      3108080.26     13930756.86      3108187.64     13930345.52
      3108297.05     13930221.47      3108380.64     13929923.12
#Sta/Elev= 30
  4499.8  100.11  4679.8  100.16  4709.8  100.53  4749.8  100.01  4889.8  100.52
  4899.8  100.23  4924.9   97.53  4944.9   92.03  4954.9   88.52  4964.9   84.67
 4969.52   81.56 4986.42   79.16 4989.48    79.2 4994.08   76.38 5001.25   76.21
  5005.6   76.81 5010.59   78.49 5013.65   78.61 5021.53   80.44  5034.9   85.13
  5054.9   92.92  5064.9   95.98  5084.9  100.05  5090.3   100.4  5140.3   99.89
  5200.3  100.63  5220.3  100.36  5240.3  101.07  5310.3  100.52  5400.2  100.78
#Mann= 3 ,-1 , 0
  4499.8     .06       0  4899.8     .04       0  5090.3     .06       0
Bank Sta=4899.8,5090.3
Exp/Cntr=0.5,0.3

Type RM Length L Ch R = 1 ,21806.1 ,56.9,56.9,56.9
BEGIN DESCRIPTION:
Upstream Section of Bridge/Culvert/Weir
END DESCRIPTION:
XS GIS Cut Line= 3
      3108185.36     13930804.97      3108326.54     13930253.91
      3108411.55     13929924.49
#Sta/Elev= 20
  4544.8  102.36  4723.3  101.18  4774.6  101.57  4877.7  101.17    4927  100.17
  4944.3   96.14  4956.8   89.63  4986.3   78.09  4988.3   76.78  5000.3   76.54
    5011   76.55  5013.8   78.09  5040.1   89.05  5057.9      96    5061  102.85
  5103.3   102.7  5156.4  102.36  5213.4  102.39  5414.7  101.66    5452  102.06
#Mann= 4 ,-1 , 0
  4544.8     .06       0    4927     .04       0    5061     .06       0
    5452     .99       0
#XS Ineff= 2 , 0
       0 4934.68   102.2 5059.11       0   102.1
Permanent Ineff=
       F       F
Bank Sta=4927,5061
Exp/Cntr=0.5,0.3

Type RM Length L Ch R = 3 ,21777.6 ,,,
BEGIN DESCRIPTION:
UNION PACIFIC RAILROAD
Structure ID: K111-00-00-S11
END DESCRIPTION:
Bridge Culvert--1,0,-1,-1, 0
Deck Dist Width WeirC Skew NumUp NumDn MinLoCord MaxHiCord MaxSubmerge Is_Ogee
10,36.9,2.6,0, 44, 44, , , 0.95, 0, ,,,
  4544.8  4644.8  4675.8  4694.8  4717.3  4723.3    4766  4774.6    4818  4827.6
  4874.2  4877.7 4902.59  4902.7 4902.81    4927 4934.87 4934.96  4944.3  4956.8
  4986.3  4988.3  5000.3    5011  5013.8  5040.1  5057.9 5058.79  5058.9    5061
 5062.49  5062.6 5062.71  5103.3  5106.3  5156.4  5161.6  5213.4  5216.2  5266.9
  5267.8  5414.7  5441.6    5452
   102.4   102.2  102.45   102.6  103.85  103.85  103.83  103.84  103.89  103.91
  103.99  103.99     104   106.4   106.4  106.43  106.44  106.44  106.46  106.47
  106.52  106.52  106.53  106.55  106.55  106.59  106.61  106.61  106.62  106.62
  106.62  106.62  104.22  104.06  104.05  103.93  103.92  103.86  103.86  104.26
  104.27  102.69   102.4   102.1
   102.4  101.71   101.5  101.39  101.26  101.22  101.54  101.61  101.46  101.43
  101.23  101.21  100.71   100.7   100.7  100.21   98.38   98.36   98.36   98.37
   98.42   98.42   98.43   98.45   98.45   98.49   98.51   98.51   98.25  102.89
  102.88  102.88  102.88  102.74  102.72   102.4   102.4  102.43  102.42  102.24
  102.24   101.7  101.99   102.1
  4544.8  4644.8  4675.8  4694.8  4717.3  4723.3    4766  4774.6    4818  4827.6
  4874.2  4877.7 4902.59  4902.7 4902.81    4927 4934.87 4934.96  4944.3  4956.8
  4986.3  4988.3  5000.3    5011  5013.8  5040.1  5057.9 5058.79  5058.9    5061
 5062.49  5062.6 5062.71  5103.3  5106.3  5156.4  5161.6  5213.4  5216.2  5266.9
  5267.8  5414.7  5441.6    5452
  102.46   102.2  102.45   102.6  103.85  103.85  103.83  103.84  103.89  103.91
  103.99  103.99     104   106.4   106.4  106.43  106.44  106.44  106.46  106.47
  106.52  106.52  106.53  106.55  106.55  106.59  106.61  106.61  106.62  106.62
  106.62  106.62  104.22  104.06  104.05  103.93  103.92  103.86  103.86  104.26
  104.27  102.69   102.4  102.16
  102.46  101.77  101.56  101.45  101.32  101.28   101.6  101.67  101.52  101.49
  101.29  101.27  100.77  100.76  100.76  100.27   98.44   98.42   98.42   98.43
   98.48   98.48   98.49   98.51   98.51   98.55   98.57   98.57   98.31  102.95
  102.94  102.94  102.94   102.8  102.78  102.46  102.46  102.49  102.48   102.3
   102.3  101.76  102.05  102.16
Pier Skew, UpSta & Num, DnSta & Num=  ,4956.8, 2 ,4956.8, 2 , 0 , 0 , 0 ,,
     2.1     2.1
   88.26   99.37
     2.1     2.1
   88.32   99.43
Pier Skew, UpSta & Num, DnSta & Num=  ,4984.3, 2 ,4984.3, 2 , 0 , 0 , 0 ,,
     2.1     2.1
    77.5   99.42
     2.1     2.1
   77.56   99.48
Pier Skew, UpSta & Num, DnSta & Num=  ,5011.6, 2 ,5011.6, 2 , 0 , 0 , 0 ,,
     2.1     2.1
   75.59   99.45
     2.1     2.1
   75.65   99.51
Pier Skew, UpSta & Num, DnSta & Num=  ,5040.1, 2 ,5040.1, 2 , 0 , 0 , 0 ,,
     2.1     2.1
   87.65   99.49
     2.1     2.1
   87.71   99.55
BR Coef= 1 , 1 , 1 ,1.05, 0 ,,,0.8,0,1.2,0,
WSPro=,,,, 1 ,,,, 0 ,,,, 0 ,,,,-1 ,-1 ,-1 , 0 , 0 , 0 , 0 , 0
BR U #Sta/Elev= 44
  4544.8   102.4  4644.8  101.71  4675.8   101.5  4694.8  101.39  4717.3  101.26
  4723.3  101.22    4766  101.54  4774.6  101.61    4818  101.46  4827.6  101.43
  4874.2  101.23  4877.7  101.21 4902.59  100.71  4902.7   100.7 4902.81   100.7
    4927  100.21 4934.87   98.38 4934.96   98.36  4944.3   96.18  4956.8   89.67
  4986.3   78.13  4988.3   76.82  5000.3   76.58    5011   76.59  5013.8   78.13
  5040.1   89.09  5057.9   96.04 5058.79   98.01  5058.9   98.25    5061  102.89
 5062.49  102.88  5062.6  102.88 5062.71  102.88  5103.3  102.74  5106.3  102.72
  5156.4   102.4  5161.6   102.4  5213.4  102.43  5216.2  102.42  5266.9  102.24
  5267.8  102.24  5414.7   101.7  5441.6  101.99    5452   102.1
BR U #Mann= 4
  4544.8     .06    4927     .04    5061     .06    5452     .99
BR U Banks=4927,5061
BR D #Sta/Elev= 44
  4544.8  102.46  4644.8  101.77  4675.8  101.56  4694.8  101.45  4717.3  101.32
  4723.3  101.28    4766   101.6  4774.6  101.67    4818  101.52  4827.6  101.49
  4874.2  101.29  4877.7  101.27 4902.59  100.77  4902.7  100.76 4902.81  100.76
    4927  100.27 4934.87   98.44 4934.96   98.42  4944.3   96.24  4956.8   89.73
  4986.3   78.19  4988.3   76.88  5000.3   76.64    5011   76.65  5013.8   78.19
  5040.1   89.15  5057.9    96.1 5058.79   98.07  5058.9   98.31    5061  102.95
 5062.49  102.94  5062.6  102.94 5062.71  102.94  5103.3   102.8  5106.3  102.78
  5156.4  102.46  5161.6  102.46  5213.4  102.49  5216.2  102.48  5266.9   102.3
  5267.8   102.3  5414.7  101.76  5441.6  102.05    5452  102.16
BR D #Mann= 4
  4544.8     .06    4927     .04    5061     .06    5452     .99
BR D Banks=4927,5061
BC Design=,, 0 ,, 0 ,,,,,,
BC HTab HWMax=102.85

Type RM Length L Ch R = 1 ,21749.2 ,24.7,24.7,24.65
BEGIN DESCRIPTION:
Downstream Section of Bridge/Culvert/Weir
END DESCRIPTION:
XS GIS Cut Line= 3
      3108228.24     13930830.24      3108369.42      13930279.2
      3108454.42     13929949.81
#Sta/Elev= 20
  4544.8  102.38  4723.3   101.2  4774.6  101.59  4877.7  101.19    4927  100.19
  4944.3   96.16  4956.8   89.65  4986.3   78.11  4988.3    76.8  5000.3   76.56
    5011   76.57  5013.8   78.11  5040.1   89.07  5057.9   96.02    5061  102.87
  5103.3  102.72  5156.4  102.38  5213.4  102.41  5414.7  101.68    5452  102.08
#Mann= 4 ,-1 , 0
  4544.8     .06       0    4927     .04       0    5061     .06       0
    5452     .99       0
#XS Ineff= 2 , 0
       0 4934.68   102.2 5059.11       0   102.1
Permanent Ineff=
       F       F
Bank Sta=4927,5061
Exp/Cntr=0.5,0.3

Type RM Length L Ch R = 1 ,21724.5 ,61,61,61
BEGIN DESCRIPTION:
Upstream Section of Bridge/Culvert/Weir
END DESCRIPTION:
XS GIS Cut Line= 4
      3108258.74     13930831.79       3108322.5      13930555.5
      3108380.19      13930320.2      3108475.83     13929960.42
#Sta/Elev= 30
  4575.9      97  4675.9    96.4  4755.8   97.48  4805.8   96.68  4835.8   97.08
  4845.8   96.28  4859.2   96.38  4879.3   98.68  4899.3  100.08  4919.3   99.78
  4929.2   98.78 4933.81   97.64  4941.4   95.64  4988.1   77.17  5001.3   76.38
  5004.3   77.56  5013.7   78.29  5059.9   95.95 5065.01   96.43  5099.3   99.68
  5141.6   97.38  5161.6   97.08  5191.6   97.78  5231.7    96.7  5361.7    96.6
  5371.7    96.9  5391.7    99.9  5401.7   100.5  5441.7    96.8    5474    96.7
#Mann= 5 ,-1 , 0
  4575.9     .06       0 4933.81    .045       0  4941.4     .04       0
  5059.9    .045       0 5065.01     .06       0
#XS Ineff= 2 , 0
       0  4931.4    96.7  5069.9       0    99.9
Permanent Ineff=
       F       F
Bank Sta=4941.4,5059.9
Exp/Cntr=0.5,0.3

Type RM Length L Ch R = 3 ,21694.0 ,,,
BEGIN DESCRIPTION:
HARDY ROAD
Structure ID: K111-00-00-S10
END DESCRIPTION:
Bridge Culvert--1,0,-1,-1, 0
Deck Dist Width WeirC Skew NumUp NumDn MinLoCord MaxHiCord MaxSubmerge Is_Ogee
10,41,2.6,0, 52, 52, , , 0.95, 0, ,,,
  4575.9  4742.3  4755.8  4795.9  4805.8  4815.8  4835.8  4845.8  4857.4  4859.2
  4869.3  4879.3  4899.3  4909.2  4918.7  4919.3 4920.29  4920.4 4920.51  4929.2
 4933.81  4933.9  4939.3  4941.4  4959.2  4980.3  4986.2  4988.1  5001.3  5004.3
  5011.9  5013.7  5020.6  5059.9 5064.79  5064.9 5065.01 5077.43 5077.54  5079.3
  5089.3  5099.3  5101.6  5107.6  5111.6  5141.6  5161.6  5167.7  5181.6  5191.6
  5223.2    5474
    99.7    99.7   99.74   99.84   99.87   99.89   99.94   99.97     100  100.01
  100.05  100.09  100.17  100.21  100.24  100.25  100.25  103.05  103.05  103.05
  103.05  103.05  103.05  103.05  103.05  103.05  103.05  103.05  103.05  103.05
  103.05  103.05  103.05  103.05  103.05  103.05  100.25  100.22  100.22  100.21
  100.19  100.16  100.16  100.14  100.13  100.03   99.96   99.94   99.93   99.92
    99.9    99.9
                                                                                
                                                                                
           97.55   97.55   97.55   97.55   97.55   97.55   97.55   97.55   97.55
   97.55   97.55   97.55   97.55   97.55   97.55   97.55   97.52
                                                                                
                
  4575.9  4742.3  4755.8  4795.9  4805.8  4815.8  4835.8  4845.8  4857.4  4859.2
  4869.3  4879.3  4899.3  4909.2  4918.7  4919.3 4920.29  4920.4 4920.51  4929.2
 4933.81  4933.9  4939.3  4941.4  4959.2  4980.3  4986.2  4988.1  5001.3  5004.3
  5011.9  5013.7  5020.6  5059.9 5064.79  5064.9 5065.01 5077.43 5077.54  5079.3
  5089.3  5099.3  5101.6  5107.6  5111.6  5141.6  5161.6  5167.7  5181.6  5191.6
  5223.2    5474
    99.7    99.7   99.74   99.84   99.87   99.89   99.94   99.97     100  100.01
  100.05  100.09  100.17  100.21  100.24  100.25  100.25  103.05  103.05  103.05
  103.05  103.05  103.05  103.05  103.05  103.05  103.05  103.05  103.05  103.05
  103.05  103.05  103.05  103.05  103.05  103.05  100.25  100.22  100.22  100.21
  100.19  100.16  100.16  100.14  100.13  100.03   99.96   99.94   99.93   99.92
    99.9    99.9
                                                                                
                                                                                
           97.55   97.55   97.55   97.55   97.55   97.55   97.55   97.55   97.55
   97.55   97.55   97.55   97.55   97.55   97.55   97.55   97.52
                                                                                
                
Pier Skew, UpSta & Num, DnSta & Num=  ,4980.3, 2 ,4980.3, 2 , 0 , 0 , 0 ,,
     1.2     1.2
   79.06   98.55
     1.2     1.2
   79.14   98.63
Pier Skew, UpSta & Num, DnSta & Num=  ,5020.6, 2 ,5020.6, 2 , 0 , 0 , 0 ,,
     1.2     1.2
   79.53   98.55
     1.2     1.2
   79.61   98.63
BR Coef= 1 , 1 , 1 ,1.05, 0 ,,,0.8,0,1.2,0,
WSPro=,,,, 1 ,,,, 0 ,,,, 0 ,,,,-1 ,-1 ,-1 , 0 , 0 , 0 , 0 , 0
BC Design=,, 0 ,, 0 ,,,,,,
BC HTab HWMax=100.5

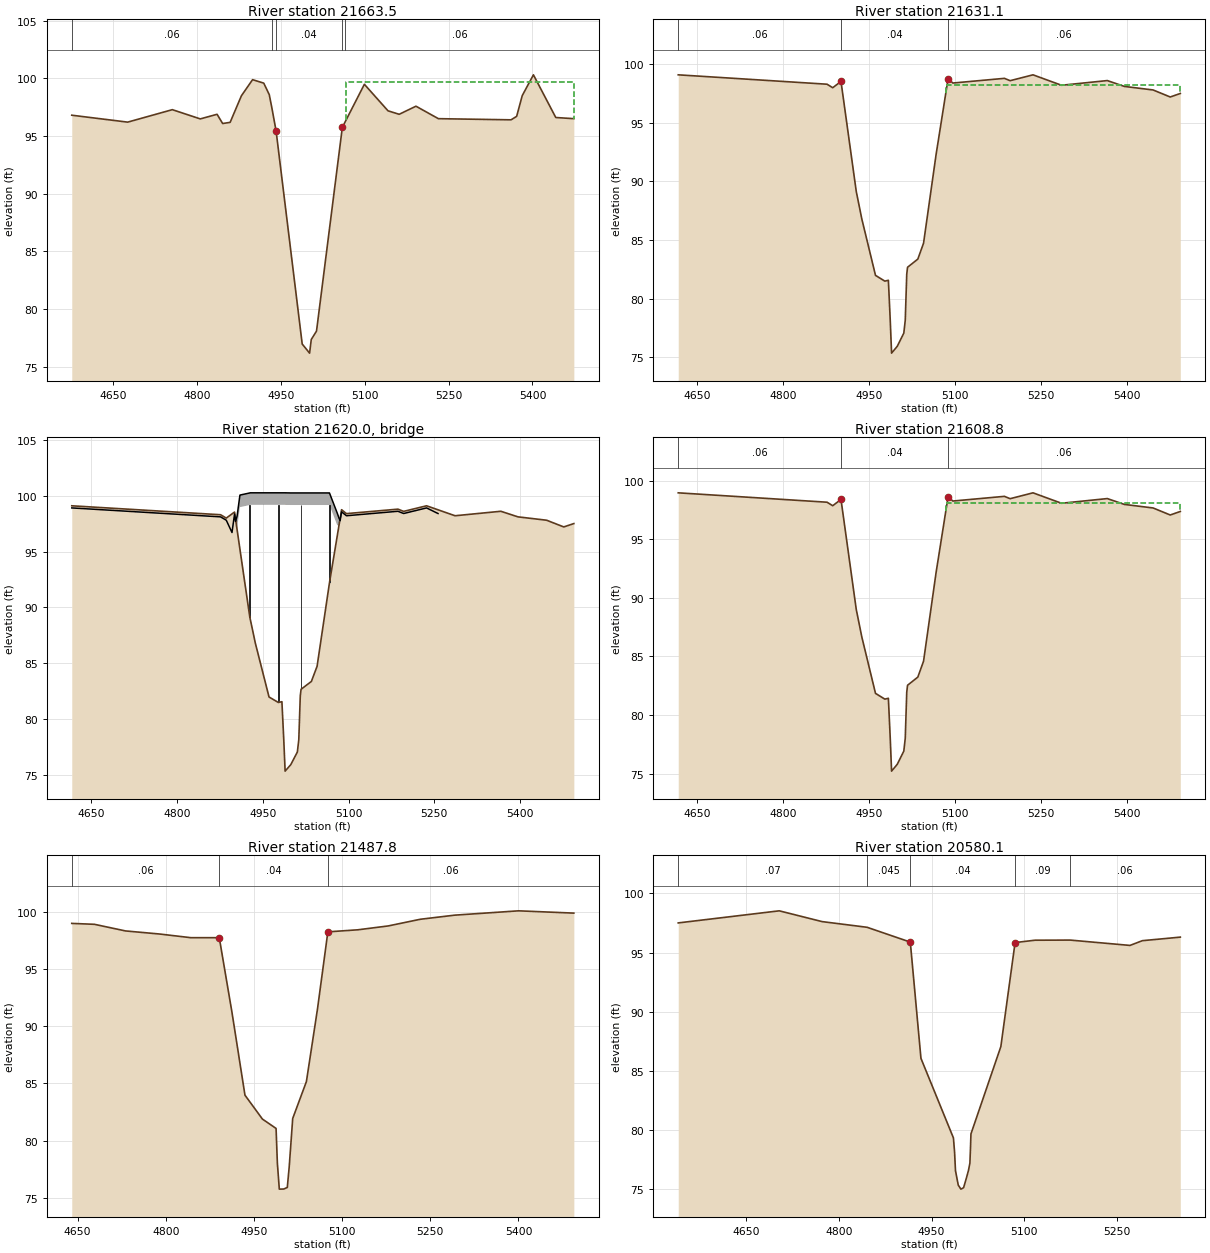
Type RM Length L Ch R = 1 ,21663.5 ,32.4,32.4,32
BEGIN DESCRIPTION:
Downstream Section of Bridge/Culvert/Weir
END DESCRIPTION:
XS GIS Cut Line= 4
       3108311.8     13930853.53      3108375.51     13930577.44
      3108433.08     13930342.62      3108528.64     13929983.12
#Sta/Elev= 30
  4575.9   96.81  4675.9   96.21  4755.8   97.29  4805.8   96.49  4835.8   96.89
  4845.8   96.09  4859.2   96.19  4879.3   98.49  4899.3   99.89  4919.3   99.59
  4929.2   98.59 4933.81   97.45  4941.4   95.45  4988.1   76.98  5001.3   76.19
  5004.3   77.37  5013.7    78.1  5059.9   95.76 5065.01   96.24  5099.3   99.49
  5141.6   97.19  5161.6   96.89  5191.6   97.59  5231.7   96.51  5361.7   96.41
  5371.7   96.71  5381.7   98.51  5401.7  100.31  5441.7   96.61    5474   96.51
#Mann= 5 ,-1 , 0
  4575.9     .06       0 4933.81    .045       0  4941.4     .04       0
  5059.9    .045       0 5065.01     .06       0
#XS Ineff= 2 , 0
       0 4934.73   96.51 5066.57       0   99.71
Permanent Ineff=
       F       F
Bank Sta=4941.4,5059.9
Exp/Cntr=0.5,0.3

Type RM Length L Ch R = 1 ,21631.1 ,22.3,22.3,22.3
BEGIN DESCRIPTION:
Upstream Section of Bridge/Culvert/Weir
END DESCRIPTION:
XS GIS Cut Line= 2
      3108331.52     13930839.07      3108560.75     13929991.99
#Sta/Elev= 30
  4616.4   99.09  4876.4   98.29  4886.4   97.99 4900.83   98.53 4927.53   89.14
 4937.23    86.8 4961.13   81.99 4977.43    81.5 4983.63   81.57 4986.83   78.23
 4989.23   75.36 4999.13   75.94 5010.63   77.07 5013.13   78.16 5015.73   82.08
 5017.13   82.68 5035.13   83.38 5045.13   84.74 5067.03    92.3 5087.93   98.74
  5096.4   98.39  5186.4   98.79  5196.4   98.59  5236.4   99.09  5286.2    98.2
  5366.2    98.6  5396.2    98.1  5446.2    97.8  5476.2    97.2  5493.8    97.5
#Mann= 3 ,-1 , 0
  4616.4     .06       0 4900.83     .04       0 5087.93     .06       0
#XS Ineff= 2 , 0
       0    4905    96.7    5084       0    98.2
Permanent Ineff=
       F       F
Bank Sta=4900.83,5087.93
Exp/Cntr=0.5,0.3

Type RM Length L Ch R = 3 ,21620.0 ,,,
BEGIN DESCRIPTION:
PL1_K111-00-00-S9
END DESCRIPTION:
Bridge Culvert--1,0,-1,-1, 0
Deck Dist Width WeirC Skew NumUp NumDn MinLoCord MaxHiCord MaxSubmerge Is_Ogee
10,1,2.6,0, 38, 38, , , 0.95, 0, ,,,
  4616.4  4876.4  4886.4  4896.4 4900.83 4902.68 4905.14 4905.23 4905.33 4910.23
 4910.33 4927.53 4928.03 4937.23 4961.13 4977.43 4983.63 4986.83 4989.23 4999.13
 5010.63 5013.13 5015.73 5017.13 5035.13 5045.13 5066.73 5067.03 5080.23 5083.22
 5083.33 5085.33 5087.93  5096.4  5186.4  5196.4  5236.4  5256.4
    98.9    98.1    97.8    96.7   98.34    97.7   98.14   98.16   98.18  100.04
  100.05  100.24  100.25  100.25  100.25  100.25  100.25  100.25  100.25  100.24
  100.24  100.24  100.24  100.24  100.24  100.24  100.24   100.2   98.45   98.02
      98   97.76   98.55    98.2    98.6    98.4    98.9    98.4
    98.9    98.1    97.8    96.7   98.34   97.69   96.82   97.08    97.1   98.96
   98.97   99.16   99.17   99.17   99.17   99.17   99.17   99.17   99.17   99.16
   99.16   99.16   99.16   99.16   99.16   99.16   99.16   99.12   97.37    97.1
   97.13   97.75   98.55    98.2    98.6    98.4    98.9    98.4
  4616.4  4876.4  4886.4  4896.4 4900.83 4902.68 4905.14 4905.23 4905.33 4910.23
 4910.33 4927.53 4928.03 4937.23 4961.13 4977.43 4983.63 4986.83 4989.23 4999.13
 5010.63 5013.13 5015.73 5017.13 5035.13 5045.13 5066.73 5067.03 5080.23 5083.22
 5083.33 5085.33 5087.93  5096.4  5186.4  5196.4  5236.4  5256.4
    98.9    98.1    97.8    96.7   98.34    97.7   98.14   98.16   98.18  100.04
  100.05  100.24  100.25  100.25  100.25  100.25  100.25  100.25  100.25  100.24
  100.24  100.24  100.24  100.24  100.24  100.24  100.24   100.2   98.45   98.02
      98   97.76   98.55    98.2    98.6    98.4    98.9    98.4
    98.9    98.1    97.8    96.7   98.34   97.69   96.82   97.08    97.1   98.96
   98.97   99.16   99.17   99.17   99.17   99.17   99.17   99.17   99.17   99.16
   99.16   99.16   99.16   99.16   99.16   99.16   99.16   99.12   97.37    97.1
   97.13   97.75   98.55    98.2    98.6    98.4    98.9    98.4
Pier Skew, UpSta & Num, DnSta & Num=  ,4927.5, 2 ,4927.5, 2 , 0 , 0 , 0 ,,
     1.4     1.4
   87.78  100.17
     1.4     1.4
   87.78  100.17
Pier Skew, UpSta & Num, DnSta & Num=  ,4977.4, 2 ,4977.4, 2 , 0 , 0 , 0 ,,
     1.4     1.4
   80.32  100.17
     1.4     1.4
   80.32  100.17
Pier Skew, UpSta & Num, DnSta & Num=  ,5017.1, 2 ,5017.1, 2 , 0 , 0 , 0 ,,
     1.4     1.4
   81.19  100.16
     1.4     1.4
   81.19  100.16
Pier Skew, UpSta & Num, DnSta & Num=  ,5067, 2 ,5067, 2 , 0 , 0 , 0 ,,
     1.4     1.4
   90.87  100.16
     1.4     1.4
   90.87  100.16
BR Coef= 1 , 1 , 1 ,1.25, 0 ,,,0.8,0,2,0,
WSPro=,,,, 1 ,,,, 0 ,,,, 0 ,,,,-1 ,-1 ,-1 , 0 , 0 , 0 , 0 , 0
BC Design=,, 0 ,, 0 ,,,,,,
BC HTab HWMax=99.09

Type RM Length L Ch R = 1 ,21608.8 ,91,121,140
BEGIN DESCRIPTION:
Downstream Section of Bridge/Culvert/Weir
END DESCRIPTION:
XS GIS Cut Line= 2
      3108352.81     13930842.24      3108582.04     13929995.16
#Sta/Elev= 30
  4616.4   98.95  4876.4   98.15  4886.4   97.85 4900.83   98.39 4927.53      89
 4937.23   86.66 4961.13   81.85 4977.43   81.36 4983.63   81.43 4986.83   78.09
 4989.23   75.22 4999.13    75.8 5010.63   76.93 5013.13   78.02 5015.73   81.94
 5017.13   82.54 5035.13   83.24 5045.13    84.6 5067.03   92.16 5087.93    98.6
  5096.4   98.25  5186.4   98.65  5196.4   98.45  5236.4   98.95  5286.2   98.06
  5366.2   98.46  5396.2   97.96  5446.2   97.66  5476.2   97.06  5493.8   97.36
#Mann= 3 ,-1 , 0
  4616.4     .06       0 4900.83     .04       0 5087.93     .06       0
#XS Ineff= 2 , 0
       0    4905   96.56    5084       0   98.06
Permanent Ineff=
       F       F
Bank Sta=4900.83,5087.93
Exp/Cntr=0.5,0.3

Type RM Length L Ch R = 1 ,21487.8 ,907.7,907.7,907.7
BEGIN DESCRIPTION:
Cross Section K111-00-00-X9a
END DESCRIPTION:
XS GIS Cut Line= 2
      3108370.79     13930850.31      3108797.87     13930110.72
#Sta/Elev= 25
  4640.2      99  4678.7   98.92  4731.7   98.34  4789.7   98.07  4842.7   97.75
  4891.1   97.75  4912.6   91.25  4934.8   83.97  4964.5   81.88  4987.7   81.06
  4989.9   78.05  4993.2   75.75  5000.9   75.76  5006.8    75.9  5010.1   77.73
    5016   81.93  5039.3   85.16  5058.1   91.49  5075.8   98.26  5126.9   98.44
  5178.7   98.78  5232.9   99.36  5291.3   99.72  5400.2   100.1  5494.2    99.9
#Mann= 3 ,-1 , 0
  4640.2     .06       0  4891.1     .04       0  5075.8     .06       0
Bank Sta=4891.1,5075.8
Exp/Cntr=0.3,0.1

Type RM Length L Ch R = 1 ,20580.1 ,1394,1400.2,1408
BEGIN DESCRIPTION:
Cross Section K111-00-00-X12
END DESCRIPTION:
XS GIS Cut Line= 2
      3109014.02     13931433.64      3109480.16     13930769.58
#Sta/Elev= 24
  4540.7    97.5  4703.9   98.52  4773.2   97.61  4845.9   97.13  4915.7   95.88
  4932.9   86.07  4985.4   79.35  4987.2   78.19  4988.7   76.59  4993.2   75.37
  4997.4   75.03  5001.8   75.15  5006.1   75.92  5009.7   76.61    5012   77.23
  5012.8   78.29  5013.7   79.69    5062   87.06    5085   95.84  5117.2   96.04
    5174   96.05  5270.7    95.6  5290.7      96    5352    96.3
#Mann= 5 ,-1 , 0
  4540.7     .07       0  4845.9    .045       0  4915.7     .04       0
    5085     .09       0    5174     .06       0
Bank Sta=4915.7,5085
Exp/Cntr=0.3,0.1