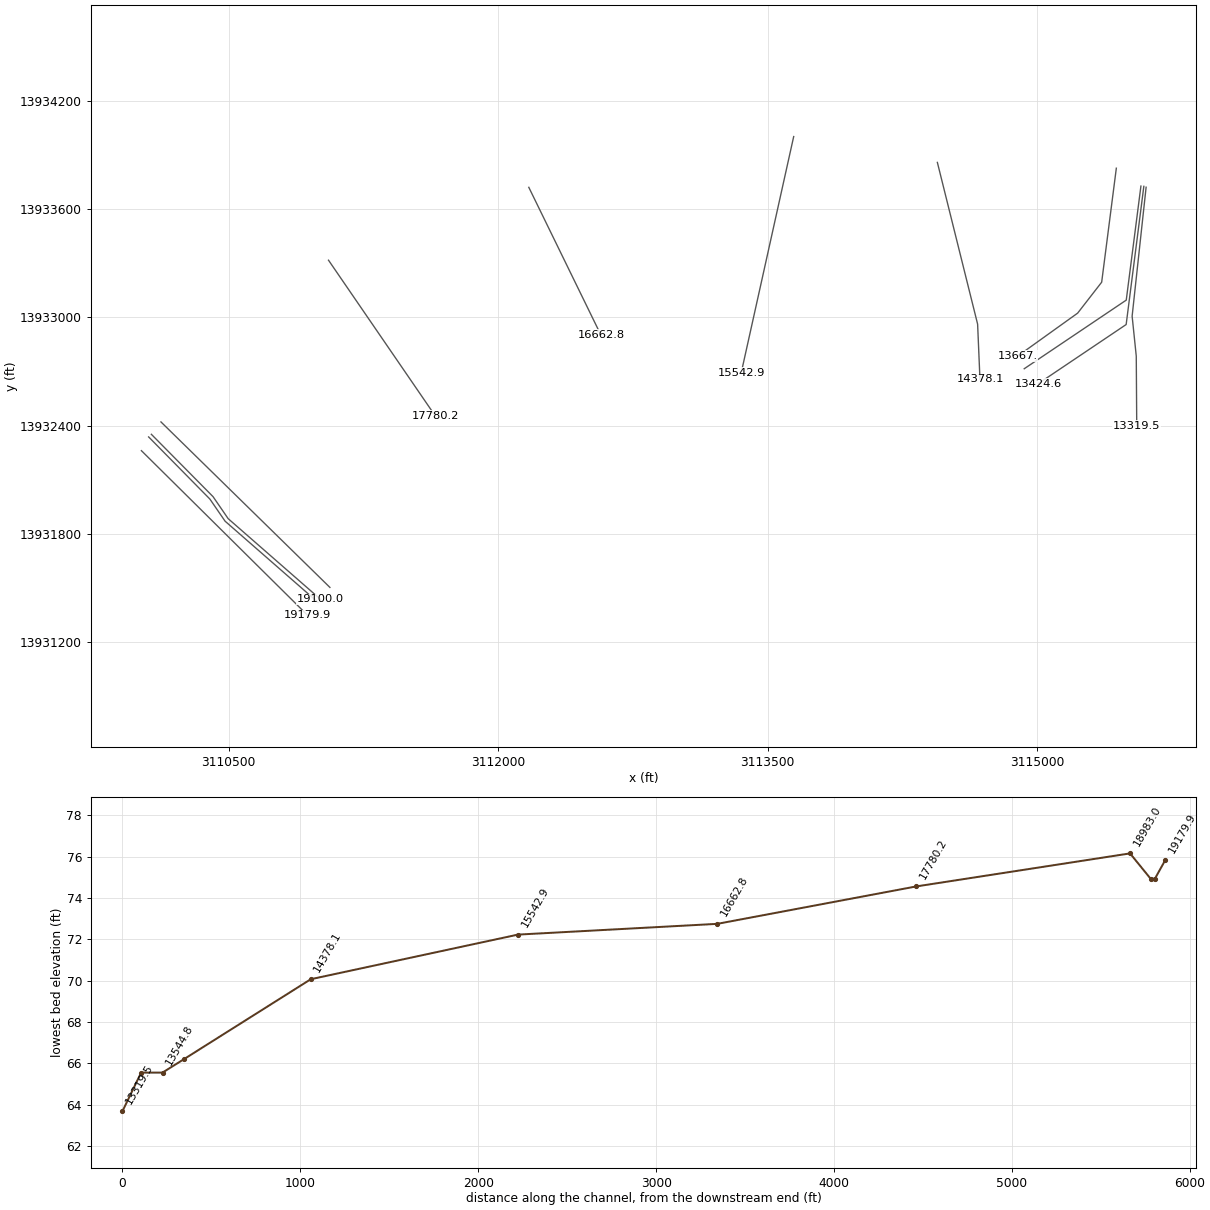
HEC-RAS study K111-00-00.prj: K111-00-00

--- K111-00-00.g02 (geometry) --- (continued)

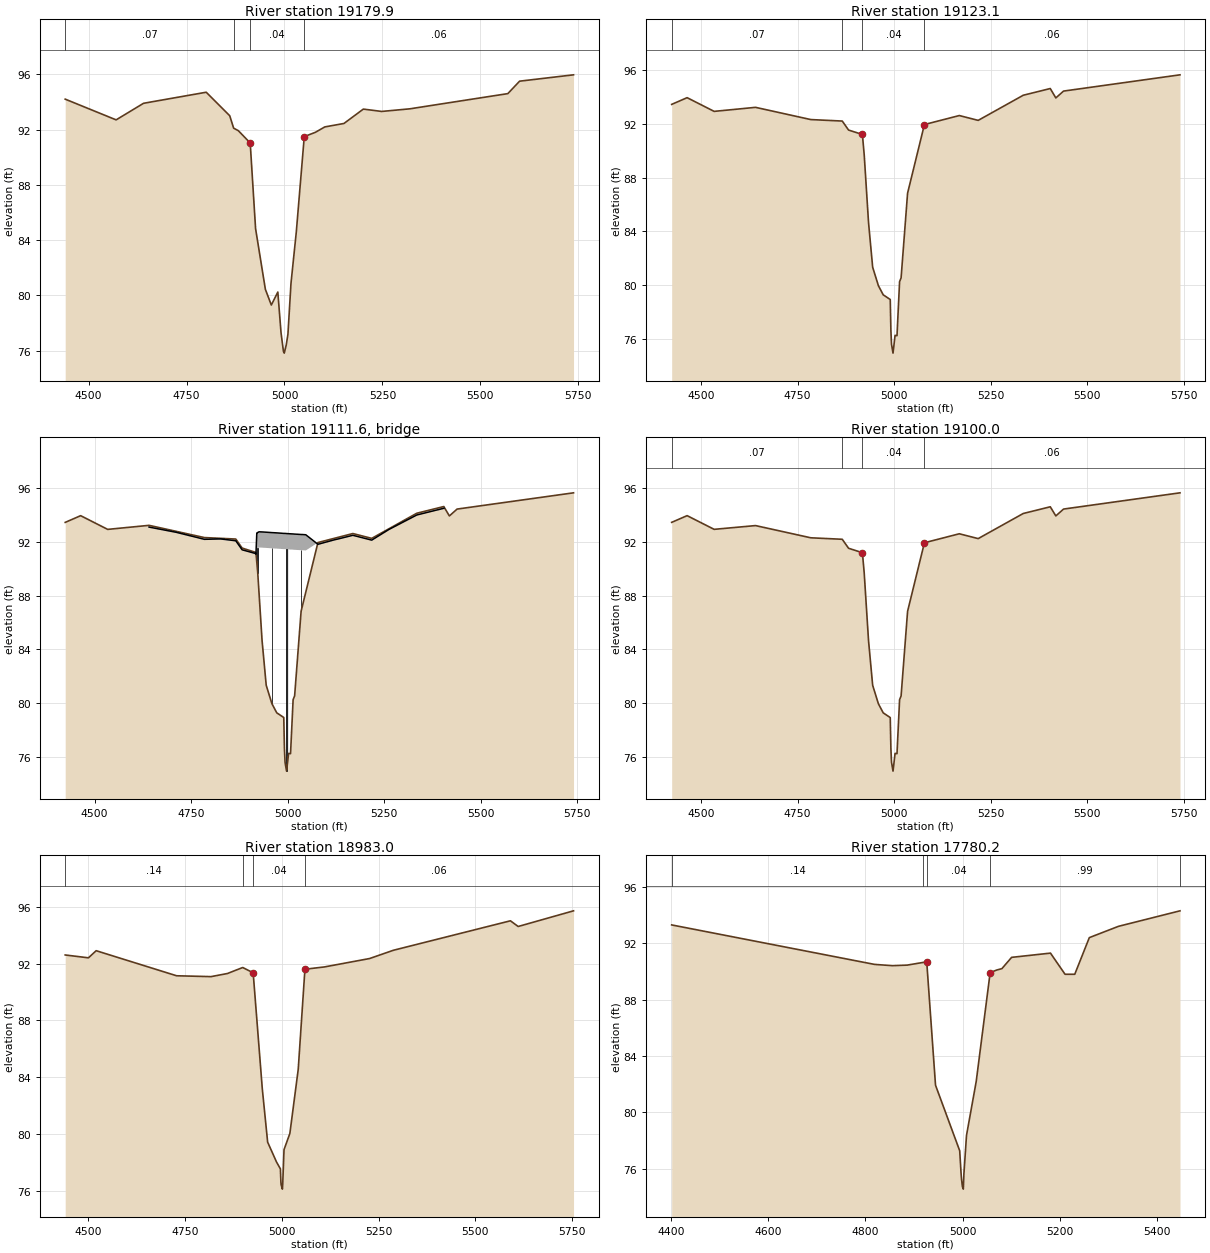
Type RM Length L Ch R = 1 ,19179.9 ,77,56.8,47
BEGIN DESCRIPTION:
Cross Section K111-00-00-X8b
END DESCRIPTION:
XS GIS Cut Line= 2
      3110014.53      13932261.5       3110938.5     13931350.31
#Sta/Elev= 30
  4440.2    94.2  4570.2    92.7  4640.2    93.9  4800.2    94.7  4860.2      93
  4870.2    92.1  4882.1   91.92  4912.5   91.03  4926.2   84.83  4951.2   80.44
  4966.4    79.3    4983   80.24  4991.2   77.29  4997.4   75.94  4999.4   75.82
  5004.5   76.41  5008.8   77.19  5016.6   80.87  5030.2    84.6  5050.5   91.49
  5078.9    91.8  5102.9   92.19  5151.8   92.44  5201.3   93.48  5248.2   93.31
  5320.2    93.5  5422.1   93.95  5570.2    94.6  5600.2    95.5  5737.9   95.96
#Mann= 4 ,-1 , 0
  4440.2     .07       0  4870.2    .045       0  4912.5     .04       0
  5050.5     .06       0
Bank Sta=4912.5,5050.5
Exp/Cntr=0.5,0.3

Type RM Length L Ch R = 1 ,19123.1 ,23.1,23.1,23.1
BEGIN DESCRIPTION:
Upstream Section of Bridge/Culvert/Weir
END DESCRIPTION:
XS GIS Cut Line= 4
      3110054.79      13932337.6      3110395.52     13931993.46
      3110480.27     13931870.75      3110997.49     13931420.97
#Sta/Elev= 30
    4424   93.45    4464   93.95    4534   92.93  4641.2   93.23 4784.41   92.32
 4865.81   92.21 4882.21   91.54 4918.01   91.21 4922.71   89.69 4933.91   84.65
 4944.61   81.33 4959.41   79.96 4971.91   79.28 4990.11   78.93 4991.81   76.62
 4993.41    75.6 4997.31   74.94 5002.61   76.26 5007.61   76.24 5014.31   80.26
 5018.21   80.54 5035.01   86.84 5078.61   91.95 5169.01   92.62 5217.91   92.26
  5334.6   94.13  5404.6   94.63    5419   93.93    5439   94.44  5740.6   95.65
#Mann= 4 ,-1 , 0
    4424     .07       0 4865.81    .045       0 4918.01     .04       0
 5078.61     .06       0
#XS Ineff= 2 , 0
       0 4908.01   91.08 5088.61       0   91.82
Permanent Ineff=
       F       F
Bank Sta=4918.01,5078.61
Exp/Cntr=0.5,0.3

Type RM Length L Ch R = 3 ,19111.6 ,,,
BEGIN DESCRIPTION:
PL1_K111-00-00-S8
END DESCRIPTION:
Bridge Culvert--1,0,-1,-1, 0
Deck Dist Width WeirC Skew NumUp NumDn MinLoCord MaxHiCord MaxSubmerge Is_Ogee
10,1,2.6,0, 38, 38, , , 0.95, 0, ,,,
  4641.2 4711.91 4763.71 4784.41 4826.31 4865.81 4882.21 4916.21 4918.01 4920.21
 4920.32 4920.41 4922.71 4926.11 4933.91 4944.61 4959.41 4971.91 4990.11 4991.81
 4993.41 4997.31 5002.61 5007.61 5008.21 5014.31 5018.21 5035.01 5037.11 5047.11
 5078.61 5119.41  5131.4 5169.01 5217.91 5262.21  5334.6  5404.6
    93.1   92.71   92.34   92.19   92.22   92.08   91.41   91.14   91.08   92.66
   92.66   92.66    92.7   92.75   92.74   92.72   92.69   92.67   92.63   92.63
   92.63   92.62   92.61    92.6    92.6   92.59   92.58   92.55   92.55   92.53
   91.82   92.14   92.22   92.49   92.13   92.92      94    94.5
    93.1   92.71   92.34   92.19   92.22   92.08   91.41   91.14   91.08   90.37
   90.33   91.49   91.53   91.58   91.57   91.55   91.52    91.5   91.46   91.46
   91.46   91.45   91.44   91.43   91.43   91.42   91.41   91.38   91.38   91.36
   90.65   92.14   92.22   92.49   92.13   92.92      94    94.5
  4641.2 4711.91 4763.71 4784.41 4826.31 4865.81 4882.21 4916.21 4918.01 4920.21
 4920.32 4920.41 4922.71 4926.11 4933.91 4944.61 4959.41 4971.91 4990.11 4991.81
 4993.41 4997.31 5002.61 5007.61 5008.21 5014.31 5018.21 5035.01 5037.11 5047.11
 5078.61 5119.41  5131.4 5169.01 5217.91 5262.21  5334.6  5404.6
    93.1   92.71   92.34   92.19   92.22   92.08   91.41   91.14   91.08   92.66
   92.66   92.66    92.7   92.75   92.74   92.72   92.69   92.67   92.63   92.63
   92.63   92.62   92.61    92.6    92.6   92.59   92.58   92.55   92.55   92.53
   91.82   92.14   92.22   92.49   92.13   92.92      94    94.5
    93.1   92.71   92.34   92.19   92.22   92.08   91.41   91.14   91.08   90.37
   90.33   91.49   91.53   91.58   91.57   91.55   91.52    91.5   91.46   91.46
   91.46   91.45   91.44   91.43   91.43   91.42   91.41   91.38   91.38   91.36
   90.65   92.14   92.22   92.49   92.13   92.92      94    94.5
Pier Skew, UpSta & Num, DnSta & Num=  ,4922.7, 2 ,4922.7, 2 , 0 , 0 , 0 ,,
     1.5     1.5
   88.22   92.54
     1.5     1.5
   88.22   92.54
Pier Skew, UpSta & Num, DnSta & Num=  ,4959.4, 2 ,4959.4, 2 , 0 , 0 , 0 ,,
     1.5     1.5
   78.79   92.52
     1.5     1.5
   78.79   92.52
Pier Skew, UpSta & Num, DnSta & Num=  ,4997.3, 2 ,4997.3, 2 , 0 , 0 , 0 ,,
     1.5     1.5
   73.94   92.45
     1.5     1.5
   73.94   92.45
Pier Skew, UpSta & Num, DnSta & Num=  ,5035, 2 ,5035, 2 , 0 , 0 , 0 ,,
     1.5     1.5
   85.43   92.38
     1.5     1.5
   85.43   92.38
BR Coef= 1 , 1 , 1 ,1.25, 0 ,,,0.8,0,2,0,
WSPro=,,,, 1 ,,,, 0 ,,,, 0 ,,,,-1 ,-1 ,-1 , 0 , 0 , 0 , 0 , 0
BC Design=,, 0 ,, 0 ,,,,,,
BC HTab HWMax=95.65

Type RM Length L Ch R = 1 ,19100.0 ,118,117,117
BEGIN DESCRIPTION:
Downstream Section of Bridge/Culvert/Weir
END DESCRIPTION:
XS GIS Cut Line= 4
        3110070.       13932352.      3110413.27     13932006.58
      3110497.38     13931884.81      3111011.75      13931437.5
#Sta/Elev= 30
    4424   93.45    4464   93.95    4534   92.93  4641.2   93.21 4784.41    92.3
 4865.81   92.19 4882.21   91.52 4918.01   91.19 4922.71   89.67 4933.91   84.63
 4944.61   81.31 4959.41   79.94 4971.91   79.26 4990.11   78.91 4991.81    76.6
 4993.41   75.58 4997.31   74.92 5002.61   76.24 5007.61   76.22 5014.31   80.24
 5018.21   80.52 5035.01   86.82 5078.61   91.93 5169.01    92.6 5217.91   92.24
  5334.6   94.11  5404.6   94.61    5419   93.93    5439   94.44  5740.6   95.65
#Mann= 4 ,-1 , 0
    4424     .07       0 4865.81    .045       0 4918.01     .04       0
 5078.61     .06       0
#XS Ineff= 2 , 0
       0 4911.34   91.08 5085.28       0   91.82
Permanent Ineff=
       F       F
Bank Sta=4918.01,5078.61
Exp/Cntr=0.5,0.3

Type RM Length L Ch R = 1 ,18983.0 ,1202.8,1202.8,1179
BEGIN DESCRIPTION:
Cross Section K111-00-00-X8a
END DESCRIPTION:
XS GIS Cut Line= 2
      3110123.39      13932420.6       3111063.5     13931503.95
#Sta/Elev= 26
  4440.5    92.6  4500.5    92.4  4520.5    92.9  4728.2   91.14  4817.2   91.08
  4859.7    91.3    4899   91.72    4926   91.35  4949.6    83.2  4963.4   79.46
  4986.4   78.06  4996.4   77.58  4997.6   76.67  4998.2   76.47  5001.5   76.16
  5002.3    76.5  5005.7   78.93  5020.8   80.07  5042.4   84.57  5059.7    91.6
    5110   91.76  5226.7   92.35  5288.2   92.93  5590.5      95  5610.5    94.6
  5753.5    95.7
#Mann= 4 ,-1 , 0
  4440.5     .14       0    4899    .045       0    4926     .04       0
  5059.7     .06       0
Bank Sta=4926,5059.7
Exp/Cntr=0.3,0.1

Type RM Length L Ch R = 1 ,17780.2 ,1118,1117.4,1105
BEGIN DESCRIPTION:
Cross Section K111-00-00-X11
END DESCRIPTION:
XS GIS Cut Line= 2
      3111055.68     13933316.45      3111649.43     13932454.47
#Sta/Elev= 25
  4401.1    93.3  4818.8    90.5  4855.7   90.41  4886.2   90.45    4919   90.64
  4926.3   90.68  4944.4   81.93  4994.2   77.28    4997   75.68  4997.9   75.29
  4999.7   74.75  5001.6   74.56  5002.9   75.67  5008.2   78.37  5028.2    82.2
  5056.9   89.92  5070.4    90.1  5081.1    90.2  5101.1      91  5181.1    91.3
  5211.1    89.8  5231.1    89.8  5261.1    92.4  5321.1    93.2  5447.8    94.3
#Mann= 5 ,-1 , 0
  4401.1     .14       0    4919    .045       0  4926.3     .04       0
  5056.9     .99       0  5447.8     .99       0
Bank Sta=4926.3,5056.9
Exp/Cntr=0.3,0.1

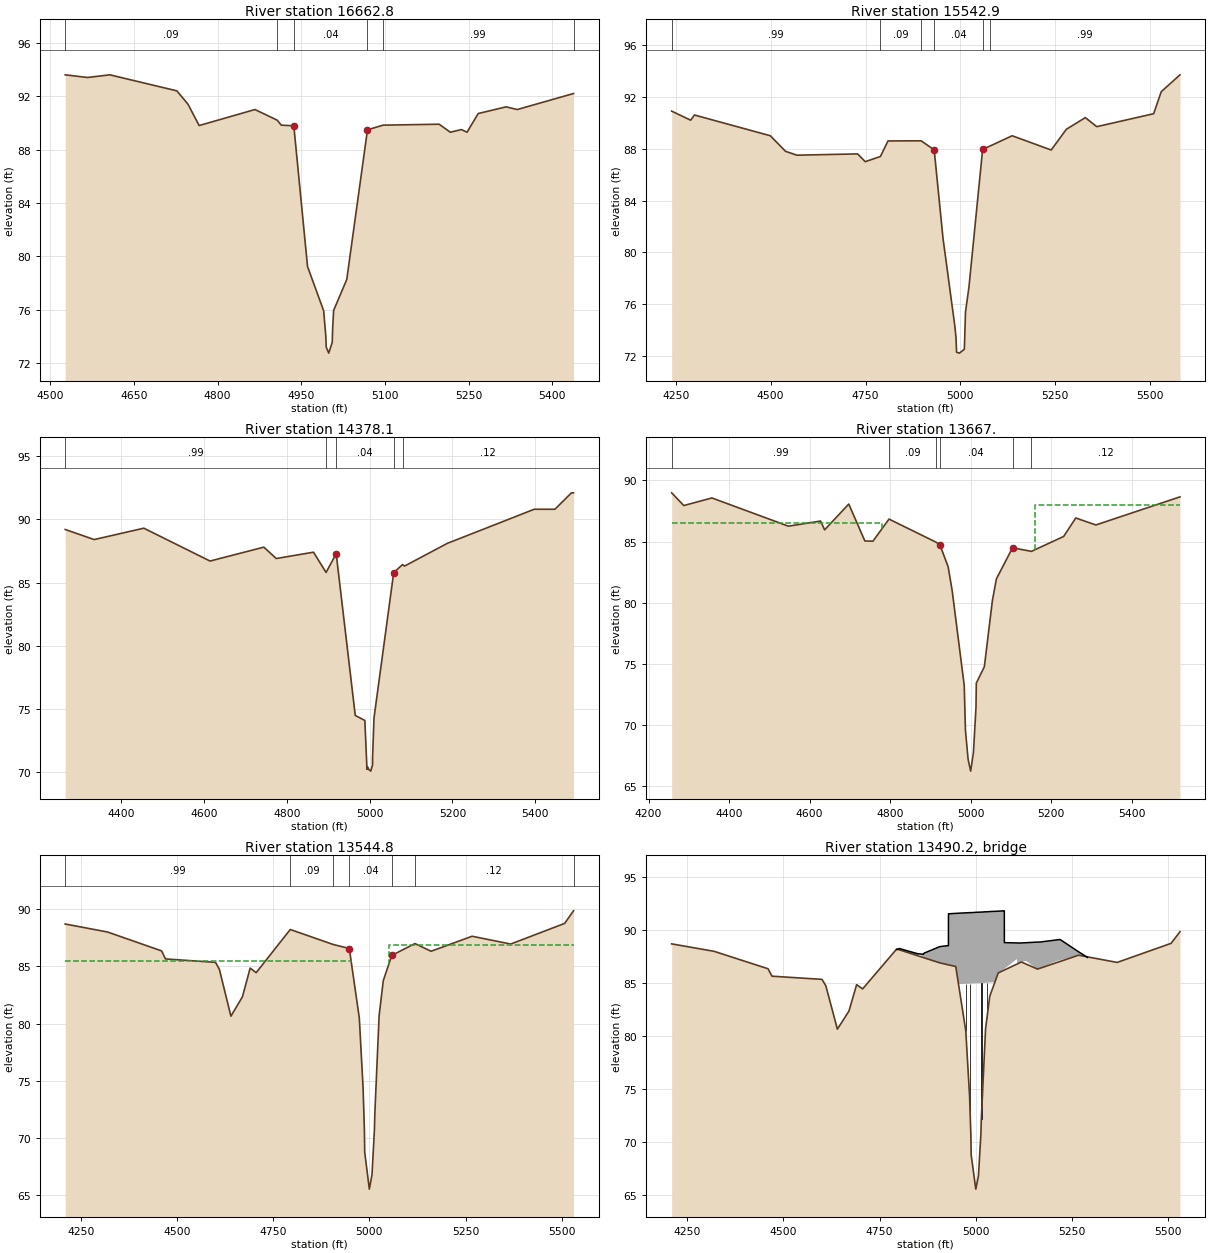
Type RM Length L Ch R = 1 ,16662.8 ,1164,1119.9,1014
BEGIN DESCRIPTION:
Cross Section K111-00-00-X10
END DESCRIPTION:
XS GIS Cut Line= 2
      3112170.27      13933720.1      3112571.31     13932902.39
#Sta/Elev= 29
    4527    93.6    4567    93.4    4607    93.6    4727    92.4    4747    91.4
    4767    89.8    4867      91    4907    90.2  4914.1   89.83  4936.6   89.78
  4961.2   79.24  4990.1   75.92  4993.9   74.05  4994.7    73.2  4999.2   72.75
  5005.5   73.57  5006.1   74.49  5007.9   75.94  5031.5   78.27  5068.6   89.48
  5096.5   89.83    5197    89.9    5217    89.3    5237    89.5    5247    89.3
    5267    90.7    5317    91.2    5337      91  5437.8    92.2
#Mann= 6 ,-1 , 0
    4527     .09       0    4907    .045       0  4936.6     .04       0
  5068.6    .045       0  5096.5     .99       0  5437.8     .99       0
Bank Sta=4936.6,5068.6
Exp/Cntr=0.3,0.1

Type RM Length L Ch R = 1 ,15542.9 ,1122,1164.8,1190
BEGIN DESCRIPTION:
Cross Section K111-00-00-X9
END DESCRIPTION:
XS GIS Cut Line= 2
      3113644.23     13934001.35      3113352.56     13932694.06
#Sta/Elev= 30
  4239.2    90.9  4289.2    90.2  4299.2    90.6  4499.2      89  4539.2    87.8
  4569.2    87.5  4729.2    87.6  4749.2      87  4789.2    87.4  4809.2    88.6
  4896.5   88.61  4930.9   87.91  4954.2   81.08  4985.5   74.28  4988.3   73.46
  4989.9    72.3  4997.4   72.23  5010.4   72.53  5013.4    75.4  5022.5   77.32
  5058.6   87.96  5079.1   88.22  5136.3      89  5239.2    87.9  5279.2    89.5
  5329.2    90.4  5359.2    89.7  5509.2    90.7  5529.2    92.4  5578.6    93.7
#Mann= 6 ,-1 , 0
  4239.2     .99       0  4789.2     .09       0  4896.5    .045       0
  4930.9     .04       0  5058.6    .045       0  5079.1     .99       0
Bank Sta=4930.9,5058.6
Exp/Cntr=0.3,0.1

Type RM Length L Ch R = 1 ,14378.1 ,777.1,711.1,648.6
BEGIN DESCRIPTION:
Cross Section K111-00-00-X8; Future residential area on left VRR
END DESCRIPTION:
XS GIS Cut Line= 3
       3114443.7     13933858.12      3114667.66     13932962.28
      3114680.68      13932657.6
#Sta/Elev= 28
  4264.3    89.2  4334.3    88.4  4454.3    89.3  4614.3    86.7  4744.3    87.8
  4774.3    86.9  4864.3    87.4  4894.7    85.8  4919.2   87.28  4965.2   74.48
  4988.4   74.08  4992.9   70.71  4993.3   70.21  4994.9   70.42  4998.4   70.18
  5002.7   70.07    5007   70.56  5007.1   71.18  5010.5   74.27  5058.1   85.78
  5079.4   86.42  5084.3    86.3  5187.7    88.1  5291.3   89.43  5397.7    90.8
  5447.7    90.8  5487.7    92.1  5492.7    92.1
#Mann= 5 ,-1 , 0
  4264.3     .99       0  4894.7    .045       0  4919.2     .04       0
  5058.1    .045       0  5079.4     .12       0
Bank Sta=4919.2,5058.1
Exp/Cntr=0.3,0.1

Type RM Length L Ch R = 1 ,13667.  ,137.1,122.2,108.8
BEGIN DESCRIPTION:
K111-00-00-S7 TOPO - W THORNE RD US - XS 4
END DESCRIPTION:
XS GIS Cut Line= 4
      3115439.59     13933826.19      3115357.97     13933194.57
      3115224.44     13933023.41      3114891.45     13932785.79
#Sta/Elev= 30
  4257.3   88.99  4287.3   87.95  4357.3   88.57  4547.3   86.26  4627.3   86.68
  4637.3   85.96  4697.3   88.07  4737.3   85.05  4757.3   85.03  4797.3   86.84
  4914.2   84.95  4924.2    84.7  4944.2   82.94  4954.2   80.99  4984.2   73.22
 4987.16   69.57 4993.85   67.18 5000.23   66.21 5007.08   67.73 5013.43   71.46
  5014.2   73.41  5034.2   74.76  5054.2   80.18  5064.2   81.95  5104.2   84.49
  5151.3    84.2  5231.3   85.42  5261.3   86.93  5311.3   86.36  5520.3   88.66
#Mann= 6 ,-1 , 0
  4257.3     .99       0  4797.3     .09       0  4914.2    .045       0
  4924.2     .04       0  5104.2     .06       0  5151.3     .12       0
#XS Ineff= 2 , 0
       0  4779.8    86.5    5160       0      88
Permanent Ineff=
       F       F
Bank Sta=4924.2,5104.2
Exp/Cntr=0.5,0.3

Type RM Length L Ch R = 1 ,13544.8 ,120.2,120.2,120.2
BEGIN DESCRIPTION:
Upstream Section of Bridge/Culvert/Weir
END DESCRIPTION:
XS GIS Cut Line= 3
      3115576.38     13933726.96      3115494.76     13933095.35
      3114927.01     13932715.26
#Sta/Elev= 30
  4209.7    88.7  4319.7      88  4460.2   86.35  4470.2   85.65  4600.2   85.35
  4610.2   84.75  4640.2   80.65  4670.2   82.35  4690.2   84.85  4705.8   84.45
  4794.4   88.22    4906   86.91  4947.8   86.56  4973.8   80.48  4983.6   74.36
    4987   70.64  4987.8   68.78  4999.8   65.55  5006.7    66.8  5013.1   70.78
  5014.1   72.15  5025.2   80.69  5036.1   83.76  5058.1   85.96  5118.3   86.99
  5160.2   86.32  5266.9   87.63  5367.1   86.95  5507.1   88.75  5530.3   89.85
#Mann= 7 ,-1 , 0
  4209.7     .99       0  4794.4     .09       0    4906    .045       0
  4947.8     .04       0  5058.1     .06       0  5118.3     .12       0
  5530.3     .99       0
#XS Ineff= 2 , 0
       0 4952.93    85.5    5050       0    86.9
Permanent Ineff=
       F       F
Bank Sta=4947.8,5058.1
Exp/Cntr=0.5,0.3

Type RM Length L Ch R = 3 ,13490.2 ,,,
BEGIN DESCRIPTION:
WW THORNE BOULEVARD
Structure ID: K111-00-00-S7
END DESCRIPTION:
Bridge Culvert--1,0,-1,-1, 0
Deck Dist Width WeirC Skew NumUp NumDn MinLoCord MaxHiCord MaxSubmerge Is_Ogee
10,89.2,2.6,0, 48, 48, , , 0.95, 0, ,,,
  4794.4    4795  4801.4  4836.1    4848  4852.7  4863.9  4865.1  4883.7    4906
 4928.69  4928.8 4928.91  4947.8 4954.16 4954.25  4957.6  4967.9  4973.8  4983.6
    4987  4987.8  4993.1  4999.8  5006.7  5013.1  5014.1  5025.2  5028.9  5036.1
  5046.5  5049.7 5049.81  5058.1 5073.79  5073.9 5074.01  5106.8  5107.4  5114.4
  5118.3  5130.2  5160.2  5167.6  5209.2    5219  5266.9  5289.9
   88.17   88.16   88.26    87.9   87.78   87.76   87.72   87.82    88.1   88.44
   88.54   91.54   91.54   91.58   91.59   91.59    91.6   91.62   91.63   91.65
   91.65   91.65   91.66   91.68   91.69    91.7    91.7   91.73   91.73   91.75
   91.77   91.77   91.77   91.79   91.82   91.82   88.82   88.79   88.79   88.78
   88.79   88.81   88.87   88.88   89.07   89.11   87.95   87.42
   88.17   88.16   88.02   87.25   87.59   87.72   87.47   87.45   87.04   86.86
   86.67   86.67   86.67   86.51   84.92   84.89    84.9   84.92   84.93   84.95
   84.95   84.95   84.96   84.98   84.99      85      85   85.03   85.03   85.05
   85.07   85.07   85.08   85.91   86.35   86.35   86.35   87.27   86.81    86.9
   86.94   87.09   86.27   86.39   87.07   87.16   87.58   87.42
  4794.4    4795  4801.4  4836.1    4848  4852.7  4863.9  4865.1  4883.7    4906
 4928.69  4928.8 4928.91  4947.8 4954.16 4954.25  4957.6  4967.9  4973.8  4983.6
    4987  4987.8  4993.1  4999.8  5006.7  5013.1  5014.1  5025.2  5028.9  5036.1
  5046.5  5049.7 5049.81  5058.1 5073.79  5073.9 5074.01  5106.8  5107.4  5114.4
  5118.3  5130.2  5160.2  5167.6  5209.2    5219  5266.9  5289.9
   88.17   88.16   88.26    87.9   87.78   87.76   87.72   87.82    88.1   88.44
   88.54   91.54   91.54   91.58   91.59   91.59    91.6   91.62   91.63   91.65
   91.65   91.65   91.66   91.68   91.69    91.7    91.7   91.73   91.73   91.75
   91.77   91.77   91.77   91.79   91.82   91.82   88.82   88.79   88.79   88.78
   88.79   88.81   88.87   88.88   89.07   89.11   87.95   87.42
   88.17   88.16   88.02   87.25   87.59   87.72   87.47   87.45   87.04   86.86
   86.67   86.67   86.67   86.51   84.92   84.89    84.9   84.92   84.93   84.95
   84.95   84.95   84.96   84.98   84.99      85      85   85.03   85.03   85.05
   85.07   85.07   85.08   85.91   86.35   86.35   86.35   87.27   86.81    86.9
   86.94   87.09   86.27   86.39   87.07   87.16   87.58   87.42
Pier Skew, UpSta & Num, DnSta & Num=  ,4973.8, 2 ,4973.8, 2 , 0 , 0 , 0 ,,
     1.3     1.3
   79.02   85.93
     1.3     1.3
    80.1   87.01
Pier Skew, UpSta & Num, DnSta & Num=  ,4984.9, 2 ,4984.9, 2 , 0 , 0 , 0 ,,
     1.2     1.2
   71.23   85.95
     1.2     1.2
   72.31   87.03
Pier Skew, UpSta & Num, DnSta & Num=  ,5014.1, 2 ,5014.1, 2 , 0 , 0 , 0 ,,
     1.2     1.2
   70.28      86
     1.2     1.2
   71.36   87.08
Pier Skew, UpSta & Num, DnSta & Num=  ,5028.9, 2 ,5028.9, 2 , 0 , 0 , 0 ,,
     1.3     1.3
    80.7   86.03
     1.3     1.3
   81.78   87.11
BR Coef= 1 , 1 , 1 ,1.25, 0 ,,,0.8,0,2,0,
WSPro=,,,, 1 ,,,, 0 ,,,, 0 ,,,,-1 ,-1 ,-1 , 0 , 0 , 0 , 0 , 0
BC Design=,, 0 ,, 0 ,,,,,,
BC HTab HWMax=89.85

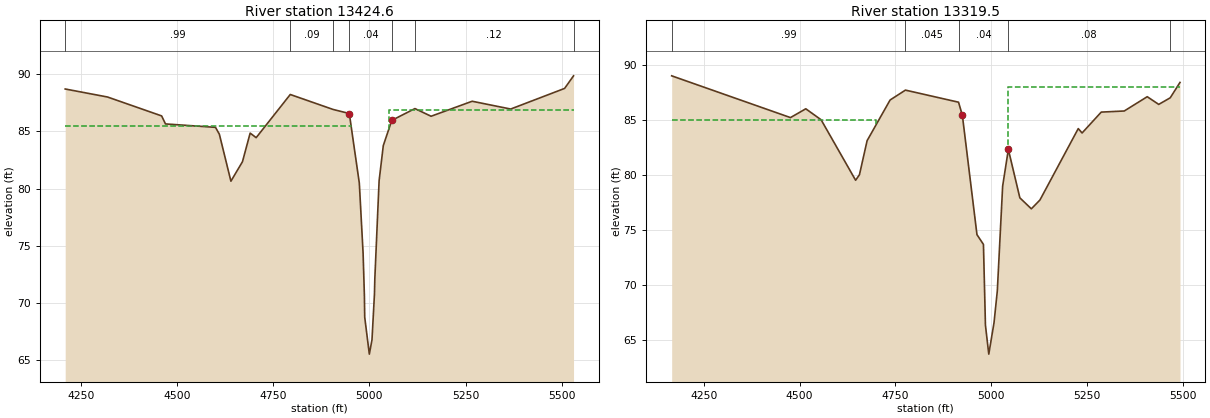
Type RM Length L Ch R = 1 ,13424.6 ,66,105.1,209
BEGIN DESCRIPTION:
Downstream Section of Bridge/Culvert/Weir
END DESCRIPTION:
XS GIS Cut Line= 3
      3115592.62     13933725.69      3115494.21      13932960.1
      3115006.12     13932633.35
#Sta/Elev= 30
  4209.7    88.7  4319.7      88  4460.2   86.35  4470.2   85.65  4600.2   85.35
  4610.2   84.75  4640.2   80.65  4670.2   82.35  4690.2   84.85  4705.8   84.45
  4794.4   88.22    4906   86.91  4947.8   86.56  4973.8   80.48  4983.6   74.36
    4987   70.64  4987.8   68.78  4999.8   65.55  5006.7    66.8  5013.1   70.78
  5014.1   72.15  5025.2   80.69  5036.1   83.76  5058.1   85.96  5118.3   86.99
  5160.2   86.32  5266.9   87.63  5367.1   86.95  5507.1   88.75  5530.3   89.85
#Mann= 7 ,-1 , 0
  4209.7     .99       0  4794.4     .09       0    4906    .045       0
  4947.8     .04       0  5058.1     .06       0  5118.3     .12       0
  5530.3     .99       0
#XS Ineff= 2 , 0
       0 4952.93    85.5    5050       0    86.9
Permanent Ineff=
       F       F
Bank Sta=4947.8,5058.1
Exp/Cntr=0.5,0.3

Type RM Length L Ch R = 1 ,13319.5 ,44,78.5,114
BEGIN DESCRIPTION:
Cross Section K111-00-00-X6b
END DESCRIPTION:
XS GIS Cut Line= 4
       3115605.3     13933720.82      3115527.46     13933006.43
      3115550.48      13932785.2      3115553.08     13932399.78
#Sta/Elev= 30
  4166.2      89  4476.2    85.2  4516.2      86  4556.2      85  4646.2    79.5
  4656.2      80  4676.2    83.1  4736.2    86.8  4776.2    87.7  4914.8    86.6
  4924.8    85.4  4962.9   74.55  4979.8   73.66    4985   66.31  4993.7   63.68
  5007.4   66.54    5016   69.44  5029.9   78.97  5044.8    82.3  5074.8    77.9
  5104.8    76.9  5127.2    77.7  5227.2    84.2  5237.2    83.8  5287.2    85.7
  5347.2    85.8  5407.2    87.1  5437.2    86.4  5467.2      87  5492.7    88.4
#Mann= 5 ,-1 , 0
  4166.2     .99       0  4776.2    .045       0  4914.8     .04       0
  5044.8     .08       0  5467.2     .99       0
#XS Ineff= 2 , 0
       0    4700      85  5043.3       0      88
Permanent Ineff=
       F       F
Bank Sta=4924.8,5044.8
Exp/Cntr=0.5,0.3