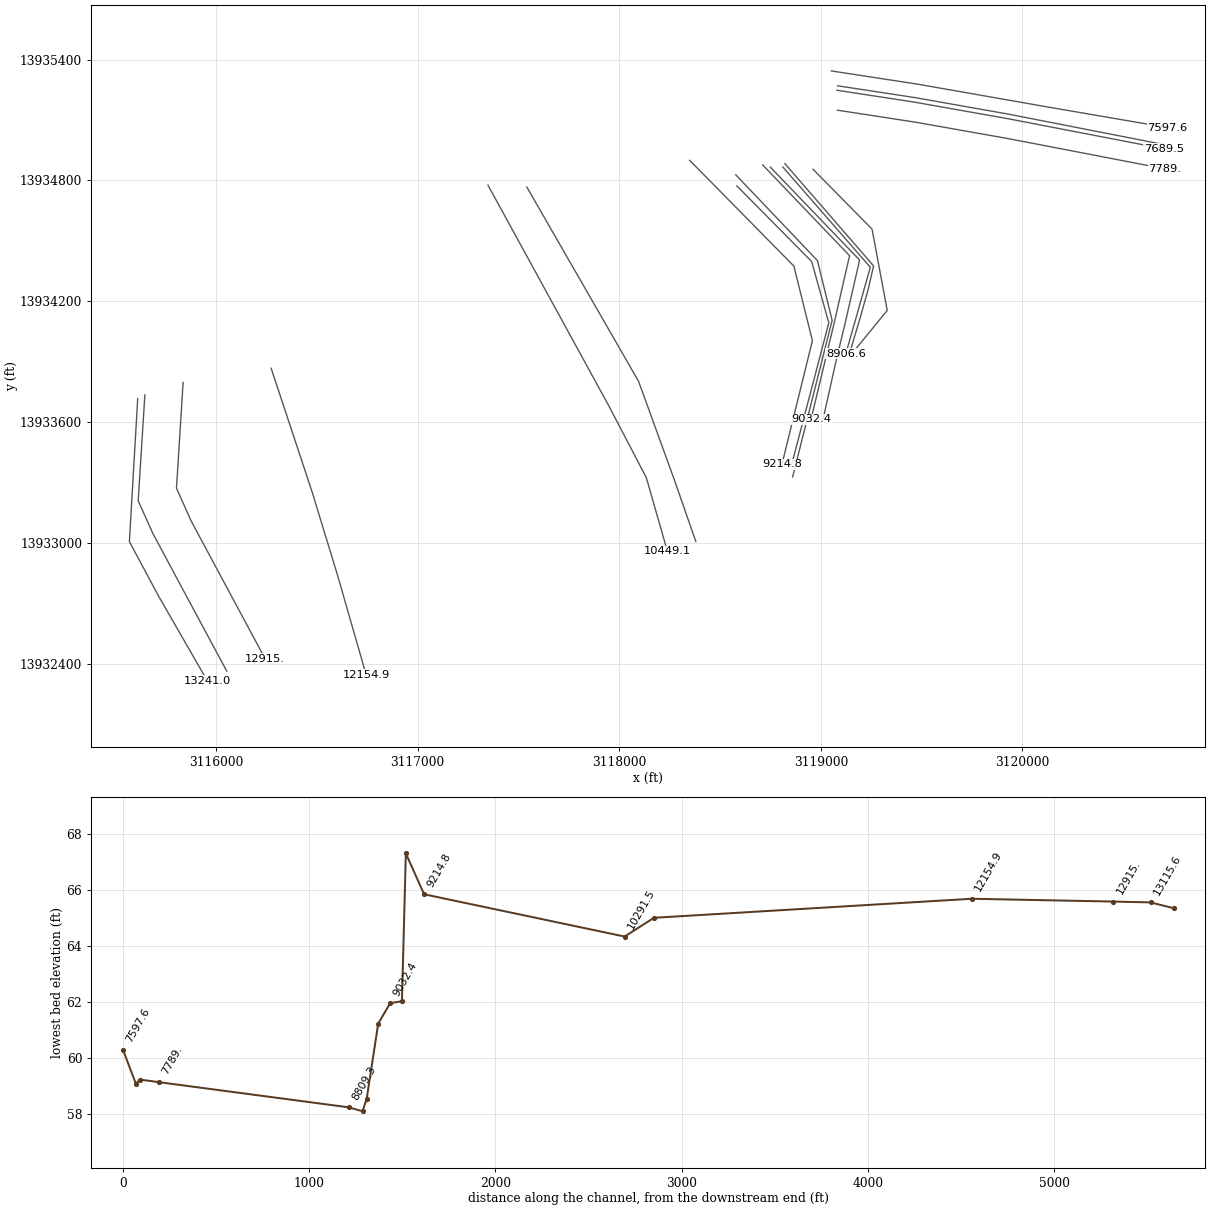
HEC-RAS study K111-00-00.prj: K111-00-00

--- K111-00-00.g02 (geometry) --- (continued)

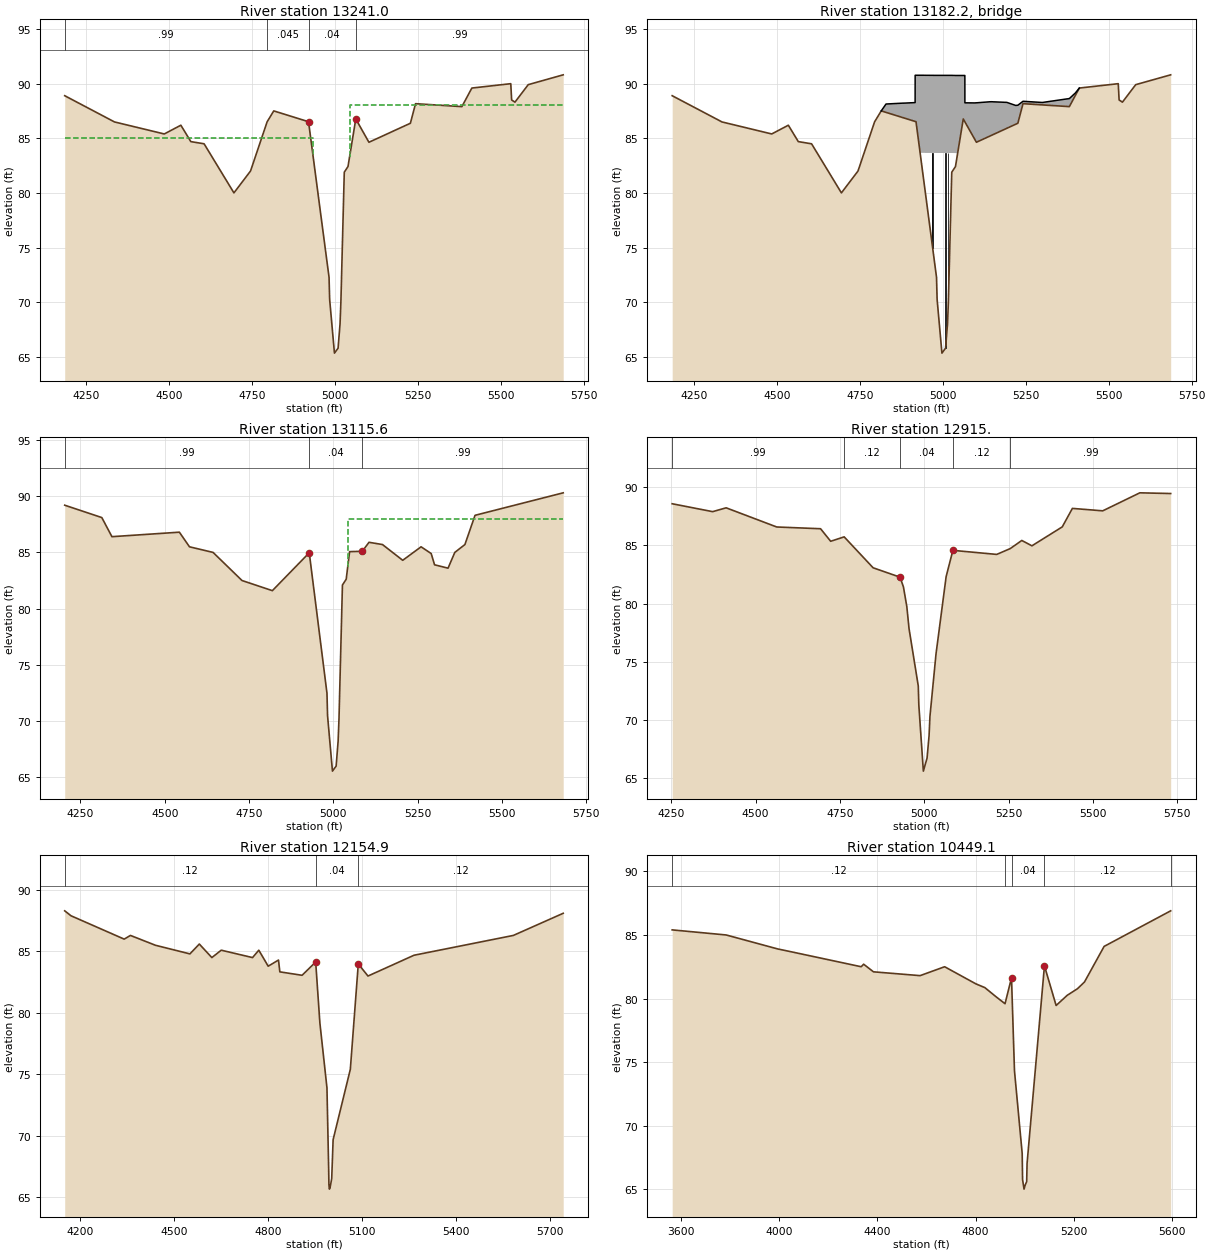
Type RM Length L Ch R = 1 ,13241.0 ,125.4,125.4,125.4
BEGIN DESCRIPTION:
Upstream Section of Bridge/Culvert/Weir
END DESCRIPTION:
XS GIS Cut Line= 4
      3115610.85       13933718.      3115569.62     13933008.58
      3115713.95     13932739.07      3115955.99     13932318.28
#Sta/Elev= 30
  4184.7   88.89  4334.7   86.49  4484.7   85.39  4534.7   86.19  4564.7   84.69
  4604.7   84.49  4694.6      80  4744.6      82  4794.6    86.5  4814.6    87.5
  4919.4   86.51  4981.2   72.28    4983   70.26  4997.5   65.34  5008.4   65.79
  5014.3      68  5016.9   70.02  5027.1   81.89  5038.3   82.41  5061.8   86.76
  5101.4   84.63  5226.3   86.37  5241.8   88.16  5381.5   87.89  5411.5   89.59
  5528.8   89.99  5531.4    88.5  5541.4    88.3  5581.4    89.9  5686.8    90.8
#Mann= 4 ,-1 , 0
  4184.7     .99       0  4794.6    .045       0  4919.4     .04       0
  5061.8     .99       0
#XS Ineff= 2 , 0
       0 4932.84      85 5042.87       0      88
Permanent Ineff=
       F       F
Bank Sta=4919.4,5061.8
Exp/Cntr=0.5,0.3

Type RM Length L Ch R = 3 ,13182.2 ,,,
BEGIN DESCRIPTION:
ALDINE WESTFIELD ROAD
Structure ID: K111-00-00-S6
END DESCRIPTION:
Bridge Culvert--1,0,-1,-1, 0
Deck Dist Width WeirC Skew NumUp NumDn MinLoCord MaxHiCord MaxSubmerge Is_Ogee
10,97.5,2.6,0, 44, 44, , , 0.95, 0, ,,,
  4814.6    4829    4880    4882 4916.69  4916.8 4916.91  4919.4  4928.7 4931.31
  4931.4  4932.6  4933.6  4938.7  4981.2    4983  4987.3  4997.5  5008.4  5014.3
  5016.9  5027.1  5038.3 5042.35 5042.46  5048.3  5061.8 5066.49  5066.6 5066.71
  5095.8  5101.4    5140  5145.9  5184.2    5193  5219.9  5226.3  5241.8  5289.9
  5299.9  5381.5  5399.9  5411.5
    87.5   88.13   88.21   88.21   88.26   90.76   90.76   90.76   90.76   90.76
   90.76   90.76   90.76   90.76   90.75   90.75   90.75   90.75   90.75   90.75
   90.75   90.75   90.74   90.74   90.74   90.74   90.74   90.74   90.74   88.24
   88.23   88.24   88.33   88.34   88.29   88.28      88   88.02   88.38   88.29
   88.27   88.63   89.15   89.59
                                                                                
                   83.66   83.66   83.65   83.65   83.65   83.65   83.65   83.65
   83.65   83.65   83.64   83.64   83.64
                                                                                
                                
  4814.6    4829    4880    4882 4916.69  4916.8 4916.91  4919.4  4928.7 4931.31
  4931.4  4932.6  4933.6  4938.7  4981.2    4983  4987.3  4997.5  5008.4  5014.3
  5016.9  5027.1  5038.3 5042.35 5042.46  5048.3  5061.8 5066.49  5066.6 5066.71
  5095.8  5101.4    5140  5145.9  5184.2    5193  5219.9  5226.3  5241.8  5289.9
  5299.9  5381.5  5399.9  5411.5
    87.5   88.13   88.21   88.21   88.26   90.76   90.76   90.76   90.76   90.76
   90.76   90.76   90.76   90.76   90.75   90.75   90.75   90.75   90.75   90.75
   90.75   90.75   90.74   90.74   90.74   90.74   90.74   90.74   90.74   88.24
   88.23   88.24   88.33   88.34   88.29   88.28      88   88.02   88.38   88.29
   88.27   88.63   89.15   89.59
                                                                                
                   83.66   83.66   83.65   83.65   83.65   83.65   83.65   83.65
   83.65   83.65   83.64   83.64   83.64
                                                                                
                                
Pier Skew, UpSta & Num, DnSta & Num=  ,4967, 2 ,4967, 2 , 0 , 0 , 0 ,,
     1.4     1.4
   74.66   84.65
     1.4     1.4
   74.66   84.65
Pier Skew, UpSta & Num, DnSta & Num=  ,4969.5, 2 ,4969.5, 2 , 0 , 0 , 0 ,,
     1.2     1.2
    74.1   84.65
     1.2     1.2
    74.1   84.65
Pier Skew, UpSta & Num, DnSta & Num=  ,5008.4, 2 ,5008.4, 2 , 0 , 0 , 0 ,,
     1.2     1.2
   64.98   84.65
     1.2     1.2
   64.98   84.65
Pier Skew, UpSta & Num, DnSta & Num=  ,5016.5, 2 ,5016.5, 2 , 0 , 0 , 0 ,,
     1.4     1.4
   68.38   84.65
     1.4     1.4
   68.38   84.65
BR Coef= 1 , 1 , 1 ,1.25, 0 ,,,0.8,0,2,0,
WSPro=,,,, 1 ,,,, 0 ,,,, 0 ,,,,-1 ,-1 ,-1 , 0 , 0 , 0 , 0 , 0
BR D #Sta/Elev= 72
  4184.7   88.89  4334.7   86.49  4414.7   86.39  4424.7   85.99  4444.7   86.29
  4484.7   85.39  4534.7   86.19  4564.7   84.69  4604.7   84.49  4654.7   81.49
  4694.6      80  4714.6    80.3  4744.6      82  4754.6    83.2  4764.6    83.9
  4774.6    84.1  4794.6    86.5  4814.6    87.5  4874.6    87.5  4894.6    86.4
  4895.7    86.4  4905.7    86.7 4916.69   86.53  4916.8   86.53 4916.91   86.53
  4919.4   86.51  4928.7   84.76 4931.31   84.04  4931.4   84.02  4932.6   83.69
  4933.6   83.45  4938.7   82.27  4981.2   72.28    4983   70.26  4987.3   68.71
  4997.5   65.34  5008.4   65.79  5014.3      68  5016.9   70.02  5027.1   81.89
  5038.3   82.41 5042.35    83.4 5042.46   83.43  5048.3   84.86  5061.8   86.76
 5066.49   86.51  5066.6    86.5 5066.71    86.5  5095.8   84.93  5101.4   84.63
    5140   85.52  5145.9   85.59  5184.2   86.01    5193   86.09  5219.9   86.32
  5226.3   86.37  5241.8   88.16  5289.9   88.07  5299.9   88.05  5381.5   87.89
  5399.9   88.93  5411.5   89.59  5419.9   89.45  5441.5   89.09    5454   89.22
  5528.8   89.99  5531.4    88.5  5541.4    88.3  5581.4    89.9  5661.4    90.4
  5671.4    90.3  5686.8    90.8
BR D #Mann= 4
  4184.7     .99  4794.6    .045  4919.4     .04  5061.8     .99
BR D Banks=4919.4,5061.8
BC Design=,, 0 ,, 0 ,,,,,,
BC HTab HWMax=90.8

Type RM Length L Ch R = 1 ,13115.6 ,188,200.6,201
BEGIN DESCRIPTION:
Downstream Section of Bridge/Culvert/Weir
END DESCRIPTION:
XS GIS Cut Line= 5
     3115646.338    13933736.024      3115613.28     13933211.24
      3115685.54     13933050.11      3115829.25     13932781.76
      3116052.46     13932366.51
#Sta/Elev= 30
  4203.5    89.2  4313.5    88.1  4343.5    86.4  4543.5    86.8  4573.5    85.5
  4643.5      85  4729.3    82.5  4819.3    81.6  4928.7   84.97  4981.2   72.49
    4983   70.47  4997.5   65.55  5008.4      66  5014.3   68.21  5016.9   70.23
  5027.1    82.1  5038.3   82.62  5048.3   85.07  5085.9    85.1  5105.9    85.9
  5145.9    85.7  5205.9    84.3  5260.3    85.5  5290.3    84.9  5300.3    83.9
  5340.3    83.6  5360.3      85  5390.3    85.7  5420.3    88.3  5681.8    90.3
#Mann= 3 ,-1 , 0
  4203.5     .99       0  4928.7     .04       0  5085.9     .99       0
#XS Ineff= 2 , 0
       0  4928.7   84.97 5042.87       0      88
Permanent Ineff=
       F       F
Bank Sta=4928.7,5085.9
Exp/Cntr=0.5,0.3

Type RM Length L Ch R = 1 ,12915.  ,761,760.1,548.3
BEGIN DESCRIPTION:
K111-00-00-S6 TOPO - ALDINE WESTFIELD RD DS - XS 1
END DESCRIPTION:
XS GIS Cut Line= 5
      3115836.19     13933798.33      3115803.13     13933273.54
      3115875.39     13933112.42       3116019.1     13932844.07
      3116242.31     13932428.82
#Sta/Elev= 30
  4252.5   88.59  4372.5   87.91  4412.5   88.24  4562.5   86.59  4692.5   86.44
  4722.5   85.36  4762.5   85.74  4848.3   83.08  4928.3   82.27  4938.3   81.43
  4948.3   79.74  4954.9   77.84 4982.27   72.91 4983.93   71.26 4997.33   65.58
 5008.33    66.7 5014.29   68.64 5016.91    70.3  5034.9   75.67  5064.9   82.32
  5084.9   84.58  5214.9   84.23  5254.9   84.73  5289.3   85.43  5319.3   84.97
  5409.3    86.6  5439.3   88.19  5529.3   87.98  5639.3   89.53  5730.8   89.47
#Mann= 5 ,-1 , 0
  4252.5     .99       0  4762.5     .12       0  4928.3     .04       0
  5084.9     .12       0  5254.9     .99       0
Bank Sta=4928.3,5084.9
Exp/Cntr=0.3,0.1

Type RM Length L Ch R = 1 ,12154.9 ,1619,1705.8,1705.8
BEGIN DESCRIPTION:
Cross Section K111-00-00-X7
END DESCRIPTION:
XS GIS Cut Line= 4
      3116272.76     13933868.63       3116478.1     13933248.82
      3116603.49     13932837.38      3116744.12     13932347.79
#Sta/Elev= 30
  4151.2    88.3  4171.2    87.9  4341.2      86  4361.2    86.3  4441.2    85.5
  4551.2    84.8  4581.2    85.6  4621.2    84.5  4651.2    85.1  4751.2    84.5
  4771.2    85.1  4801.2    83.8  4834.1    84.3  4838.4   83.34  4909.4   83.06
  4952.9   84.14  4966.3   79.19  4988.9   73.92  4994.4   67.29  4995.2   66.04
  4996.7   65.68  4998.8    65.8  5004.1   66.53  5008.6    69.7  5063.6   75.42
    5089   83.98    5120      83    5267   84.69  5584.3    86.3  5743.6    88.1
#Mann= 3 ,-1 , 0
  4151.2     .12       0  4952.9     .04       0    5089     .12       0
Bank Sta=4952.9,5089
Exp/Cntr=0.3,0.1

Type RM Length L Ch R = 1 ,10449.1 ,166,157.6,143
BEGIN DESCRIPTION:
Cross Section K111-00-00-X6
END DESCRIPTION:
XS GIS Cut Line= 4
      3117348.49      13934776.7      3117946.34     13933685.21
      3118133.94     13933326.31      3118238.91     13932959.77
#Sta/Elev= 28
  3564.2    85.4  3784.2      85  3994.2    83.9    4046   83.69  4334.2    82.5
  4344.2    82.7  4384.2    82.1  4574.2    81.8  4674.2    82.5  4801.7   81.15
  4837.8   80.86  4883.5   80.14  4920.2   79.59  4946.6   81.63  4958.7   74.31
  4990.1   67.81  4991.7   65.75  4997.6      65  5002.3   65.32  5008.4   65.59
    5010   67.02  5080.8   82.57  5128.4   79.45  5173.4   80.25  5215.3   80.77
  5243.9    81.3  5323.9    84.1  5595.1    86.9
#Mann= 5 ,-1 , 0
  3564.2     .12       0  4920.2    .045       0  4946.6     .04       0
  5080.8     .12       0  5595.1     .99       0
Bank Sta=4946.6,5080.8
Exp/Cntr=0.3,0.1

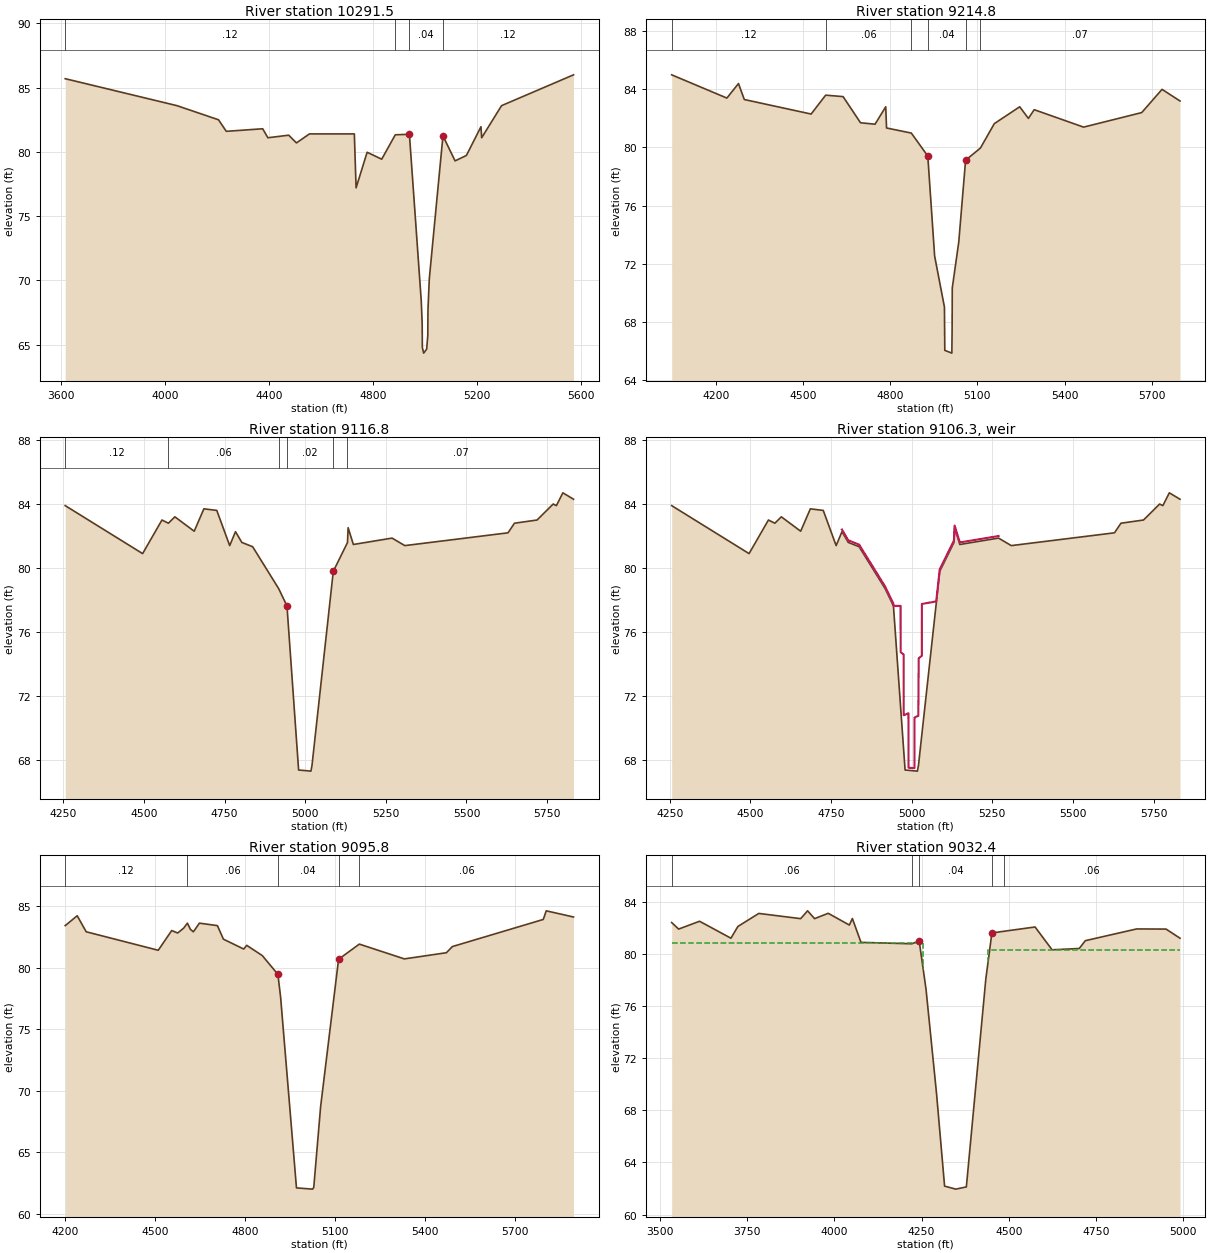
Type RM Length L Ch R = 1 ,10291.5 ,1076.7,1076.7,1087
BEGIN DESCRIPTION:
Cross Section K111-00-00-X5
END DESCRIPTION:
XS GIS Cut Line= 4
      3117541.08      13934767.6      3118095.68     13933803.52
      3118275.37     13933308.73      3118379.53     13933009.25
#Sta/Elev= 30
  3615.1    85.7  4045.1    83.6  4205.1    82.5  4235.1    81.6  4375.1    81.8
  4395.1    81.1  4475.1    81.3  4505.1    80.7  4555.1    81.4  4727.8    81.4
  4734.5    77.2    4777   79.97  4833.1   79.43  4885.3   81.33  4939.7   81.37
  4985.2   68.43  4988.8   66.66  4989.5   64.77  4994.5   64.33  5006.1   64.64
  5010.4   65.68  5011.1   67.67  5016.2   70.11  5068.8   81.25  5115.4    79.3
    5159   79.72  5215.1   81.96  5217.8    81.1  5294.3    83.6  5571.3      86
#Mann= 4 ,-1 , 0
  3615.1     .12       0  4885.3     .06       0  4939.7     .04       0
  5068.8     .12       0
Bank Sta=4939.7,5068.8
Exp/Cntr=0.3,0.1

Type RM Length L Ch R = 1 ,9214.8  ,96,98,98
BEGIN DESCRIPTION:
Cross Section K111-00-00-X5a
END DESCRIPTION:
XS GIS Cut Line= 4
      3118349.38      13934899.7      3118866.11     13934375.25
      3118957.94     13934005.34      3118806.78     13933391.98
#Sta/Elev= 30
  4047.6      85  4237.6    83.4  4277.6    84.4  4297.6    83.3  4527.6    82.3
  4577.6    83.6  4637.6    83.5  4697.6    81.7  4747.6    81.6  4784.4    82.8
  4787.2   81.34  4872.5   80.99  4929.2   79.41  4952.7   72.53  4986.5   69.01
  4987.7   66.03    5012   65.84  5012.9   67.51  5013.4   70.32  5035.8   73.49
  5059.3   79.12  5110.4   79.96  5158.2   81.64  5245.5    82.8  5275.5      82
  5295.5    82.6  5465.5    81.4  5665.5    82.4  5735.5      84  5797.3    83.2
#Mann= 6 ,-1 , 0
  4047.6     .12       0  4577.6     .06       0  4872.5    .045       0
  4929.2     .04       0  5059.3    .045       0  5110.4     .07       0
Bank Sta=4929.2,5059.3
Exp/Cntr=0.7,0.5

Type RM Length L Ch R = 1 ,9116.8  ,21,21,21
BEGIN DESCRIPTION:
Upstream Section of Bridge/Culvert/Weir
END DESCRIPTION:
XS GIS Cut Line= 4
      3118583.54      13934772.8      3118954.33     13934397.92
      3119039.32     13934094.02      3118853.47     13933384.86
#Sta/Elev= 30
  4255.8    83.9  4495.8    80.9  4555.8      83  4575.8    82.8  4595.8    83.2
  4655.8    82.3  4685.8    83.7  4725.8    83.6  4765.8    81.4  4783.8   82.27
  4803.4    81.6    4837   81.33  4917.7   78.71  4943.4   77.63  4979.5   67.37
  5017.7    67.3    5021   67.66    5087   79.79    5131   81.59    5133   82.52
  5149.3   81.47  5269.3   81.87  5308.8    81.4  5628.8    82.2  5648.8    82.8
  5718.8      83  5768.8      84  5778.8    83.9  5798.8    84.7  5831.9    84.3
#Mann= 6 ,-1 , 0
  4255.8     .12       0  4575.8     .06       0  4917.7    .045       0
  4943.4     .02       0    5087    .045       0    5131     .07       0
#XS Ineff= 2 , 0
       0  4933.4   77.76    5097       0   79.92
Permanent Ineff=
       F       F
Bank Sta=4943.4,5087
Exp/Cntr=0.7,0.5

Type RM Length L Ch R = 5 ,9106.3  ,,,
BEGIN DESCRIPTION:
75' US RAYFORD ROAD (BIRNAMWOOD)
Structure ID: K111-00-00-S5
END DESCRIPTION:
IW Pilot Flow=0
#Inline Weir SE= 24
  4783.8    82.4  4803.4   81.73    4837   81.46  4917.7   78.84  4943.4   77.76
  4944.2   77.63  4965.6   77.63  4965.7   74.74  4975.3   74.58  4975.4   70.79
  4989.8   70.92  4990.3   67.51  5008.6   67.49  5008.8   70.65  5020.5   70.76
  5021.8   74.36  5031.3   74.51 5031.41   77.75    5076   77.91    5087   79.92
    5131   81.72    5133   82.65  5149.3    81.6  5269.3      82
IW Dist,WD,Coef,Skew,MaxSub,Min_El,Is_Ogee,SpillHt,DesHd
10,1,3,0,0.95,, 0 ,,,0,0,

Type RM Length L Ch R = 1 ,9095.8  ,79,63.4,13
BEGIN DESCRIPTION:
Cross Section FIELD_DS
Located At: 75' US RAYFORD ROAD (BIRNAMWOOD)
END DESCRIPTION:
XS GIS Cut Line= 4
      3118577.84       13934828.      3118983.07     13934402.48
      3119055.76     13934106.05      3118859.79     13933329.44
#Sta/Elev= 30
  4200.9    83.4  4240.9    84.2  4270.9    82.9  4510.9    81.4  4555.8      83
  4575.8    82.8  4595.8    83.2  4608.1    83.6  4618.1    83.1  4628.1    82.9
  4648.1    83.6  4708.1    83.4  4728.1    82.3  4795.8    81.5  4805.8    81.8
  4857.5   80.97  4909.6   79.45  4918.8   77.56  4971.5   62.12  5025.1   62.02
  5029.1   62.16    5052   68.72  5111.8   80.67    5181    81.9    5331    80.7
    5471    81.2    5491    81.7  5793.8    83.9  5803.8    84.6  5894.7    84.1
#Mann= 5 ,-1 , 0
  4200.9     .12       0  4608.1     .06       0  4909.6     .04       0
  5111.8    .045       0    5181     .06       0
Bank Sta=4909.6,5111.8
Exp/Cntr=0.7,0.5

Type RM Length L Ch R = 1 ,9032.4  ,64,64,64
BEGIN DESCRIPTION:
Upstream Section of Bridge/Culvert/Weir
END DESCRIPTION:
XS GIS Cut Line= 5
      3118711.05      13934877.5       3118980.7      13934595.8
       3119142.3     13934426.94      3119065.04     13934089.56
      3118951.28      13933616.2
#Sta/Elev= 30
  3533.1    82.4  3553.1    81.9  3613.1    82.5  3703.1    81.2  3723.1    82.1
  3783.1    83.1  3903.1    82.7  3923.1    83.3  3943.1    82.73982.244   83.11
4042.866   82.214051.526   82.714076.295   80.884222.133   80.774243.178      81
4262.836   77.294293.061   69.274316.097   62.184348.313   61.954378.538   62.12
4434.396   78.074451.804    81.64485.838   81.734575.732   82.064624.576   80.31
4702.518   80.414719.838   81.014867.062   81.91  4951.5    81.9  4991.5    81.2
#Mann= 5 ,-1 , 0
  3533.1     .06       04222.133    .045       04243.178     .04       0
4451.804    .045       04485.838     .06       0
#XS Ineff= 2 , 0
       0    4255   80.87 4440.39       0    80.3
Permanent Ineff=
       F       F
Bank Sta=4243.178,4451.804
Skew Angle= 30
Exp/Cntr=0.5,0.3

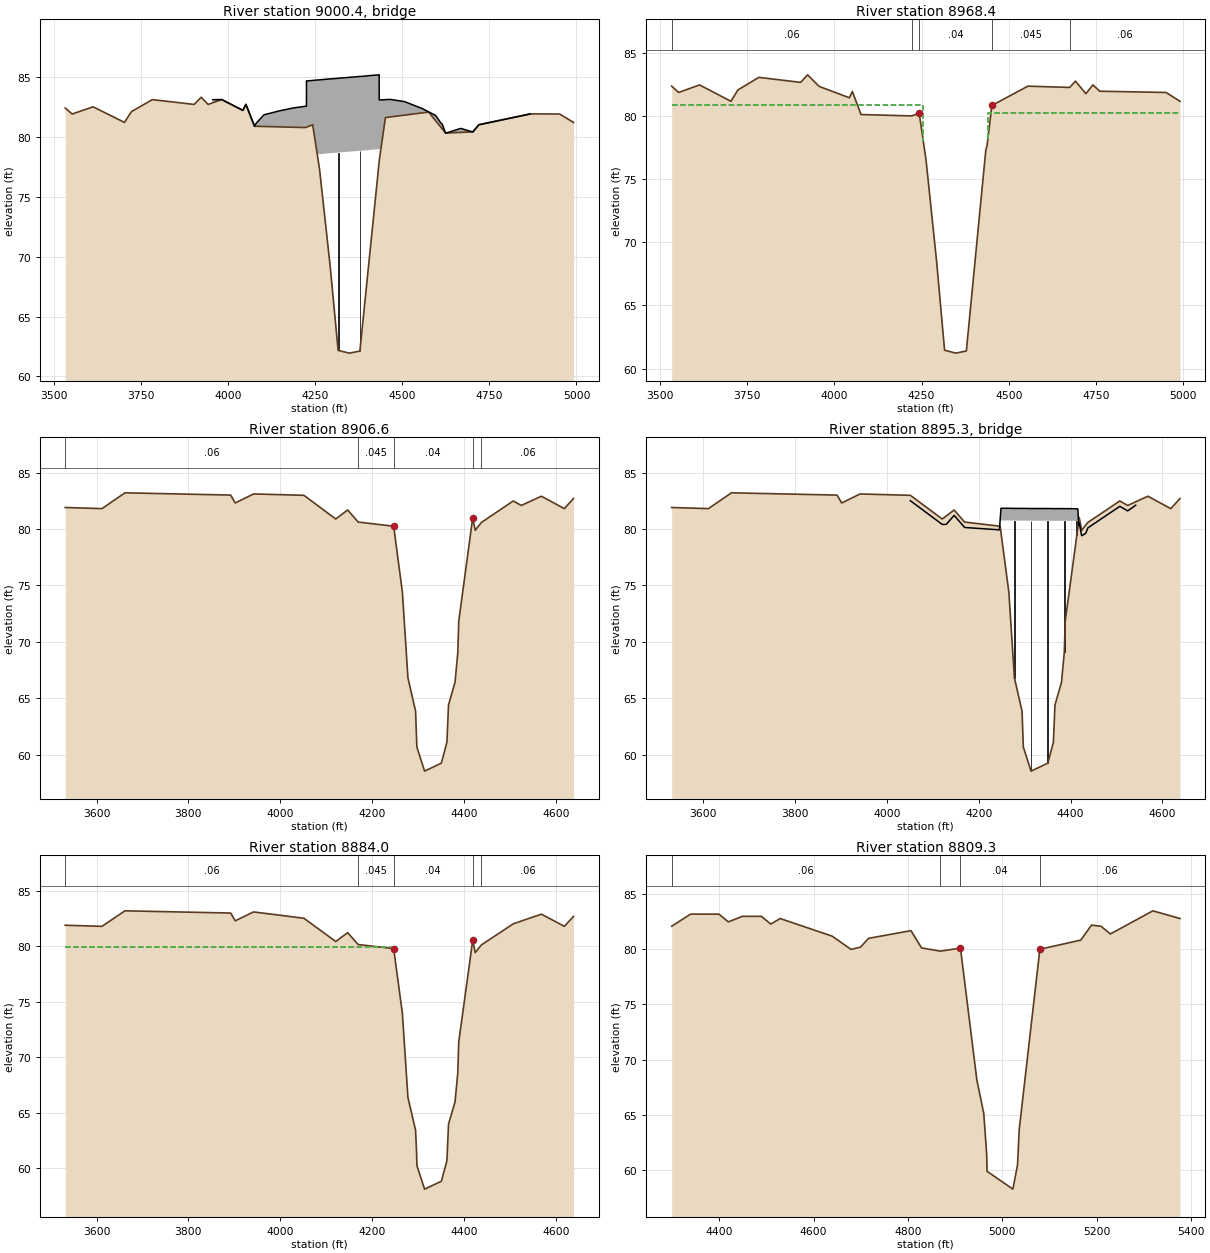
Type RM Length L Ch R = 3 ,9000.4  ,,,
BEGIN DESCRIPTION:
RAYFORD ROAD (BIRNAMWOOD)-skew structure 30 degrees
Structure ID: K111-00-00-S4
END DESCRIPTION:
Bridge Culvert--1,0,-1,-1, 0
Deck Dist Width WeirC Skew NumUp NumDn MinLoCord MaxHiCord MaxSubmerge Is_Ogee
10,44,2.6,30, 50, 50, , , 0.95, 0, ,,,
 3956.26 3982.24 4042.87 4051.53  4076.3 4080.11  4103.4 4123.15 4148.52    4170
 4188.53 4213.39 4222.13 4225.24 4225.34 4225.43 4243.18 4256.09 4256.17 4262.84
 4293.06  4316.1  4317.4 4348.31 4376.03 4378.54 4394.82 4411.71 4433.78 4433.88
 4433.97  4434.4 4438.12 4440.45 4440.55  4451.8 4466.18 4485.84 4507.14 4530.79
 4557.89 4575.73 4595.91 4610.46 4614.88 4624.58 4667.88 4702.52 4719.84 4867.06
    83.1    83.1    82.2    82.7   80.87    81.1   81.84   81.98   82.17    82.3
   82.41   82.51   82.55   82.56   84.66   84.66    84.7   84.74   84.74   84.75
   84.83   84.88   84.89   84.96   85.03   85.03   85.07   85.12   85.17   85.17
   83.07   83.07   83.08   83.08   83.08    83.1   83.12   83.03   82.93   82.66
   82.35   82.08   81.78   81.17   81.05    80.3    80.7    80.4      81    81.9
                                                                                
                                                           78.55   78.54   78.55
   78.63   78.68   78.69   78.76   78.83   78.83   78.87   78.92   78.97   78.97
   78.97   78.97   78.98   78.98      79
                                                                                
 3956.26 3982.24 4042.87 4051.53  4076.3 4080.11  4103.4 4123.15 4148.52    4170
 4188.53 4213.39 4222.13 4225.24 4225.34 4225.43 4243.18 4256.09 4256.17 4262.84
 4293.06  4316.1  4317.4 4348.31 4376.03 4378.54 4394.82 4411.71 4433.78 4433.88
 4433.97  4434.4 4438.12 4440.45 4440.55  4451.8 4466.18 4485.84 4507.14 4530.79
 4557.89 4575.73 4595.91 4610.46 4614.88 4624.58 4667.88 4702.52 4719.84 4867.06
    83.1    83.1    82.2    82.7   80.87    81.1   81.84   81.98   82.17    82.3
   82.41   82.51   82.55   82.56   84.66   84.66    84.7   84.74   84.74   84.75
   84.83   84.88   84.89   84.96   85.03   85.03   85.07   85.12   85.17   85.17
   83.07   83.07   83.08   83.08   83.08    83.1   83.12   83.03   82.93   82.66
   82.35   82.08   81.78   81.17   81.05    80.3    80.7    80.4      81    81.9
                                                                                
                                                           78.55   78.54   78.55
   78.63   78.68   78.69   78.76   78.83   78.83   78.87   78.92   78.97   78.97
   78.97   78.97   78.98   78.98      79
                                                                                
Pier Skew, UpSta & Num, DnSta & Num=  ,4316.184, 2 ,4316.184, 2 , 0 , 0 , 0 ,,
       2       2
   61.08   79.69
       2       2
   60.85   79.46
Pier Skew, UpSta & Num, DnSta & Num=  ,4378.625, 2 ,4378.625, 2 , 0 , 0 , 0 ,,
       2       2
   61.07   79.83
       2       2
   60.84    79.6
BR Coef= 1 , 1 , 1 ,1.25, 0 ,,,0.8,0,2,0,
WSPro=,,,, 1 ,,,, 0 ,,,, 0 ,,,,-1 ,-1 ,-1 , 0 , 0 , 0 , 0 , 0
BC Design=,, 0 ,, 0 ,,,,,,
BC HTab HWMax=83.3

Type RM Length L Ch R = 1 ,8968.4  ,61,61.8,61.8
BEGIN DESCRIPTION:
Downstream Section of Bridge/Culvert/Weir
END DESCRIPTION:
XS GIS Cut Line= 6
      3118749.56      13934865.9       3119019.7      13934584.7
      3119192.03     13934405.25      3119120.03     13934090.85
      3119074.11     13933899.78      3119008.95      13933606.9
#Sta/Elev= 30
  3533.1    82.4  3553.1    81.9  3613.1    82.5  3703.1    81.2  3723.1    82.1
  3783.1    83.1  3903.1    82.7  3923.1    83.33956.264   82.384042.866   81.48
4051.526   81.984076.295   80.154222.133   80.044243.178   80.274262.836   76.56
4293.061   68.544316.097   61.454348.313   61.224378.538   61.394434.396   77.34
4438.121   77.724451.804   80.87    4555    82.4    4675    82.3  4691.5    82.8
  4721.5    81.8  4741.5    82.5  4761.5      82  4951.5    81.9  4991.5    81.2
#Mann= 5 ,-1 , 0
  3533.1     .06       04222.133    .045       04243.178     .04       0
4451.804    .045       0    4675     .06       0
#XS Ineff= 2 , 0
       0    4255   80.87 4440.39       0    80.3
Permanent Ineff=
       F       F
Bank Sta=4243.178,4451.804
Skew Angle= 30
Exp/Cntr=0.5,0.3

Type RM Length L Ch R = 1 ,8906.6  ,22.6,22.6,22.6
BEGIN DESCRIPTION:
Upstream Section of Bridge/Culvert/Weir
END DESCRIPTION:
XS GIS Cut Line= 5
      3118811.21      13934866.9      3119047.88      13934595.7
      3119245.21     13934369.52      3119178.51     13934133.02
      3119123.68     13933940.65
#Sta/Elev= 30
  3531.9    81.9  3611.9    81.8  3661.9    83.2  3891.9      83  3901.9    82.3
  3941.9    83.14051.354   82.984120.635   80.884146.616   81.684169.375   80.61
4246.711   80.244265.677   74.394277.715   66.814294.343   63.864297.201   60.67
4314.001   58.544350.461   59.254362.585    61.1 4366.05    64.44380.252   66.42
4386.314   69.074388.307   71.814418.791   81.014424.091   79.884437.774   80.58
4507.056   82.484524.376   82.08  4568.1    82.9  4618.1    81.8  4638.1    82.7
#Mann= 5 ,-1 , 0
  3531.9     .06       04169.375    .045       04246.711     .04       0
4418.791    .045       04437.774     .06       0
#XS Ineff= 2 , 0
       04238.051   79.924427.451       0    79.4
Permanent Ineff=
       F       F
Bank Sta=4246.711,4418.791
Skew Angle= 30
Exp/Cntr=0.5,0.3

Type RM Length L Ch R = 3 ,8895.3  ,,,
BEGIN DESCRIPTION:
PL1_K111-00-00-S3-skew structure 30 degrees
END DESCRIPTION:
Bridge Culvert--1,0,-1,-1, 0
Deck Dist Width WeirC Skew NumUp NumDn MinLoCord MaxHiCord MaxSubmerge Is_Ogee
10,1,2.6,30, 39, 39, , , 0.95, 0, ,,,
4051.3544120.6354129.2964146.6164169.3754244.9794245.0664245.1614245.2394246.711
 4248.534250.6954265.6774277.7154294.3434296.5944297.2014314.0014335.4794350.461
4362.5854363.711 4366.054380.2524386.3144388.3074413.5944413.7684415.7594416.963
4417.0594417.6654418.7914424.0914432.7514437.7744507.0564524.3764541.697
    82.5    80.4    80.4    81.2   80.13   79.92   79.92   79.97   80.02   80.83
   81.83   81.83   81.83   81.82   81.82   81.82   81.82   81.81   81.81   81.81
    81.8    81.8    81.8    81.8    81.8    81.8   81.79   81.79   81.77   80.85
   80.77   80.31   80.53    79.4    79.6    80.1      82    81.6    82.1
    82.5    80.4    80.4    81.2   80.13   79.92   79.91    79.9    79.9   79.76
   80.75   80.75   80.75   80.74   80.74   80.74   80.74   80.73   80.73   80.73
   80.72   80.72   80.72   80.72   80.72   80.72   80.71   80.71   80.69    79.9
   79.94   80.14   80.53    79.4    79.6    80.1      82    81.6    82.1
4051.3544120.6354129.2964146.6164169.3754244.9794245.0664245.1614245.2394246.711
 4248.534250.6954265.6774277.7154294.3434296.5944297.2014314.0014335.4794350.461
4362.5854363.711 4366.054380.2524386.3144388.3074413.5944413.7684415.7594416.963
4417.0594417.6654418.7914424.0914432.7514437.7744507.0564524.3764541.697
    82.5    80.4    80.4    81.2   80.13   79.92   79.92   79.97   80.02   80.83
   81.83   81.83   81.83   81.82   81.82   81.82   81.82   81.81   81.81   81.81
    81.8    81.8    81.8    81.8    81.8    81.8   81.79   81.79   81.77   80.85
   80.77   80.31   80.53    79.4    79.6    80.1      82    81.6    82.1
    82.5    80.4    80.4    81.2   80.13   79.92   79.91    79.9    79.9   79.76
   80.75   80.75   80.75   80.74   80.74   80.74   80.74   80.73   80.73   80.73
   80.72   80.72   80.72   80.72   80.72   80.72   80.71   80.71   80.69    79.9
   79.94   80.14   80.53    79.4    79.6    80.1      82    81.6    82.1
Pier Skew, UpSta & Num, DnSta & Num=  ,4277.732, 2 ,4277.732, 2 , 0 , 0 , 0 ,,
     1.5     1.5
   65.21   81.74
     1.5     1.5
   65.21   81.74
Pier Skew, UpSta & Num, DnSta & Num=  ,4314.019, 2 ,4314.019, 2 , 0 , 0 , 0 ,,
     1.5     1.5
   57.07   81.73
     1.5     1.5
   57.07   81.73
Pier Skew, UpSta & Num, DnSta & Num=  ,4350.479, 2 ,4350.479, 2 , 0 , 0 , 0 ,,
     1.5     1.5
   57.75   81.73
     1.5     1.5
   57.75   81.73
Pier Skew, UpSta & Num, DnSta & Num=  ,4386.332, 2 ,4386.332, 2 , 0 , 0 , 0 ,,
     1.5     1.5
   67.31   81.72
     1.5     1.5
   67.31   81.72
Pier Skew, UpSta & Num, DnSta & Num=  ,4413.612, 2 ,4413.612, 2 , 0 , 0 , 0 ,,
     1.5     1.5
   77.56   81.71
     1.5     1.5
   77.56   81.71
BR Coef= 1 , 1 , 1 ,1.25, 0 ,,,0.8,0,2,0,
WSPro=,,,, 1 ,,,, 0 ,,,, 0 ,,,,-1 ,-1 ,-1 , 0 , 0 , 0 , 0 , 0
BC Design=,, 0 ,, 0 ,,,,,,
BC HTab HWMax=83.2

Type RM Length L Ch R = 1 ,8884.0  ,32,74.7,120
BEGIN DESCRIPTION:
Downstream Section of Bridge/Culvert/Weir
END DESCRIPTION:
XS GIS Cut Line= 6
      3118821.33      13934883.8      3119057.22      13934611.9
      3119261.42     13934376.48      3119234.69     13934259.97
      3119195.47     13934120.91      3119148.22     13933962.12
#Sta/Elev= 30
  3531.9    81.9  3611.9    81.8  3661.9    83.2  3891.9      83  3901.9    82.3
  3941.9    83.14051.354   82.534120.635   80.434146.616   81.234169.375   80.16
4246.711   79.794265.677   73.944277.715   66.364294.343   63.414296.594   61.34
4297.201   60.224314.001   58.094350.461    58.84362.585   60.65 4366.05   63.95
4380.252   65.974386.314   68.624388.307   71.364418.791   80.564424.091   79.43
4437.774   80.134507.056   82.03  4568.1    82.9  4618.1    81.8  4638.1    82.7
#Mann= 5 ,-1 , 0
  3531.9     .06       04169.375    .045       04246.711     .04       0
4418.791    .045       04437.774     .06       0
#XS Ineff= 2 , 0
       04240.935   79.924424.567       0    79.4
Permanent Ineff=
       F       F
Bank Sta=4246.711,4418.791
Skew Angle= 30
Exp/Cntr=0.5,0.3

Type RM Length L Ch R = 1 ,8809.3  ,951.1,1020.3,1159.2
BEGIN DESCRIPTION:
Cross Section K111-00-00-X3a
END DESCRIPTION:
XS GIS Cut Line= 5
      3118961.15      13934855.6      3119066.42      13934748.8
      3119253.86     13934558.56       3119329.2     13934155.37
      3119171.23     13933962.12
#Sta/Elev= 30
  4299.5    82.1  4339.5    83.2  4399.5    83.2  4419.5    82.5  4449.5      83
  4489.5      83  4509.5    82.3  4529.5    82.8  4639.5    81.2  4679.5      80
  4699.5    80.2  4716.6      81  4806.5    81.7  4828.9   80.13  4868.8   79.84
  4911.3   80.11    4946   68.16  4960.7   65.09  4966.9   61.39  4967.7   59.85
  5022.3   58.23  5032.2   60.42  5035.8   63.64  5079.5   80.01  5166.1   80.84
    5189    82.2    5209    82.1    5229    81.4    5319    83.5  5376.4    82.8
#Mann= 4 ,-1 , 0
  4299.5     .06       0  4868.8    .045       0  4911.3     .04       0
  5079.5     .06       0
Bank Sta=4911.3,5079.5
Exp/Cntr=0.3,0.1

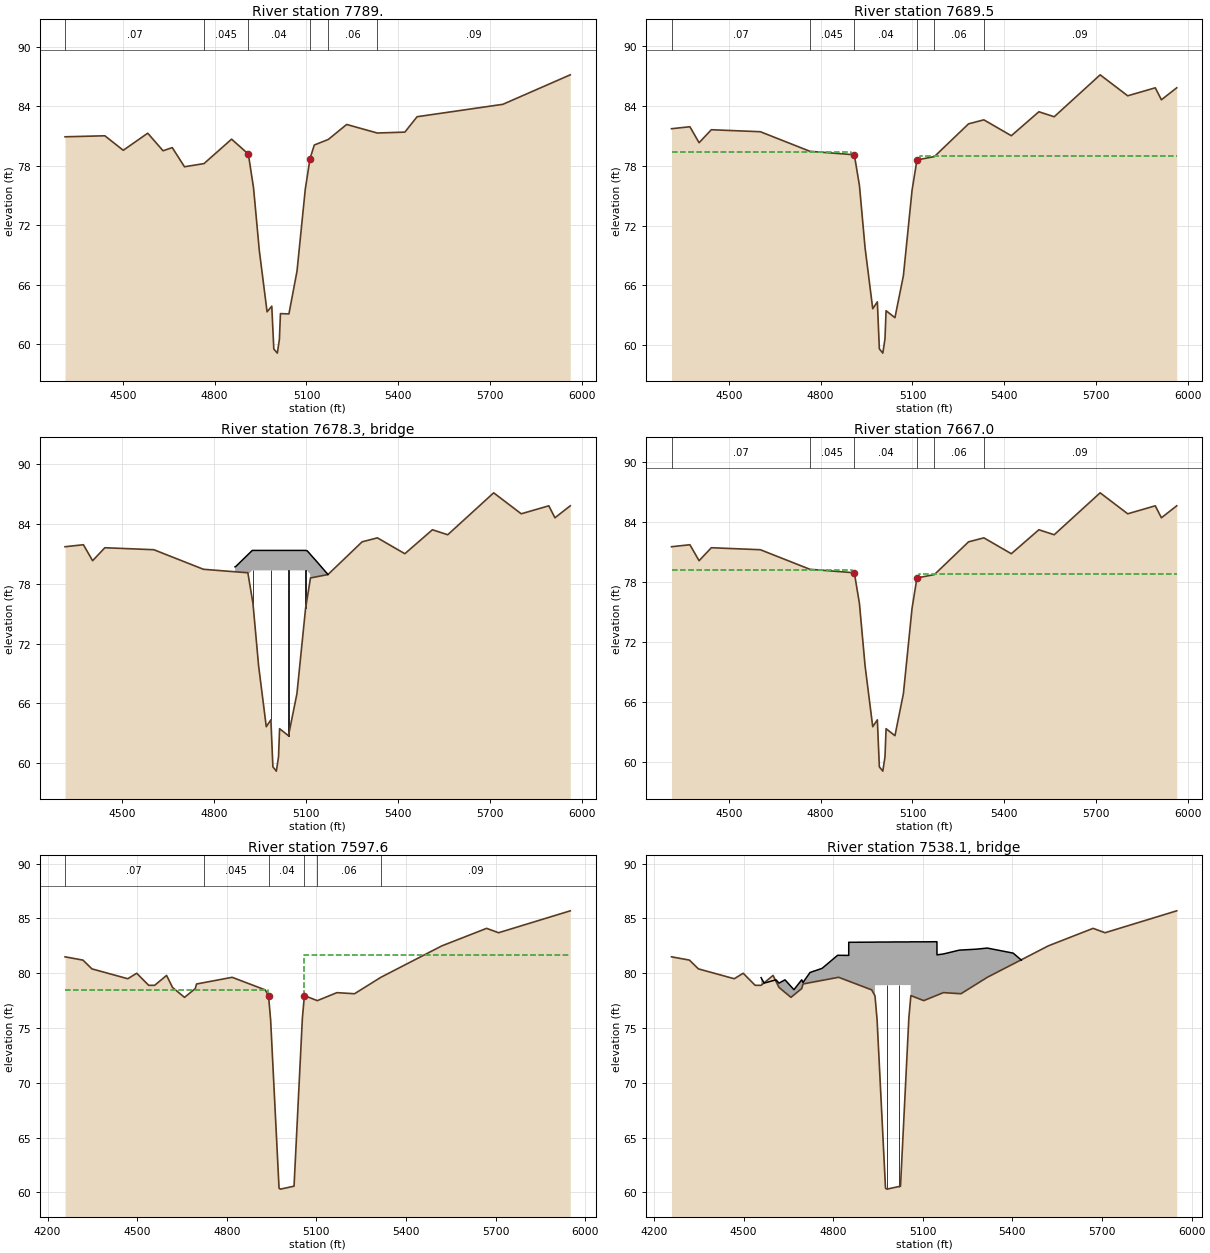
Type RM Length L Ch R = 1 ,7789.   ,98.45,99.5,116.4
BEGIN DESCRIPTION:
PL_K111-00-00-S2 TOR US - XS 4
END DESCRIPTION:
XS GIS Cut Line= 4
       3119082.3     13935148.68      3119471.44     13935088.83
      3119930.03     13935007.59      3120705.77     13934858.18
#Sta/Elev= 30
  4311.8   80.92  4441.8   81.02  4501.8   79.56  4581.8   81.28  4631.8   79.51
  4661.8   79.83  4701.8    77.9  4765.5   78.22  4855.5   80.68 4910.26   79.18
 4927.25   75.76 4945.96   69.49 4971.39   63.29 4986.75   63.86 4993.37   59.55
 5004.86   59.13 5011.65   60.52    5015   63.11 5042.75   63.08 5069.16    67.4
 5096.14   75.65 5111.44    78.7  5125.5   80.09  5171.2   80.65  5231.2   82.16
  5331.2    81.3  5421.2   81.39  5461.2   82.94  5741.2   84.19  5961.2   87.16
#Mann= 6 ,-1 , 0
  4311.8     .07       0  4765.5    .045       0 4910.26     .04       0
 5111.44    .045       0  5171.2     .06       0  5331.2     .09       0
Bank Sta=4910.26,5111.44
Exp/Cntr=0.5,0.3

Type RM Length L Ch R = 1 ,7689.5  ,22.5,22.5,22.5
BEGIN DESCRIPTION:
Upstream Section of Bridge/Culvert/Weir
END DESCRIPTION:
XS GIS Cut Line= 4
       3119079.1      13935247.7      3119468.24     13935187.93
      3119926.84     13935106.69      3120702.57      13934957.2
#Sta/Elev= 30
  4313.3    81.7  4373.3    81.9  4403.3    80.3  4443.3    81.6  4603.3    81.4
 4765.16   79.44 4910.16   79.09 4926.86   76.01 4945.26   69.77 4970.26   63.67
 4985.36   64.36 4991.86   59.65 5003.16   59.22 5010.26   60.66 5013.76   63.47
 5042.76   62.77 5070.36   66.98 5098.56   75.52 5114.56   78.57 5171.56   78.91
  5283.1   82.19  5333.1   82.59  5422.7      81  5512.7    83.4  5562.7    82.9
  5712.7    87.1  5802.7      85  5892.7    85.8  5912.7    84.6  5962.7    85.8
#Mann= 6 ,-1 , 0
  4313.3     .07       0 4765.16    .045       0 4910.16     .04       0
 5114.56    .045       0 5171.56     .06       0  5333.1     .09       0
#XS Ineff= 2 , 0
       0 4900.16   79.33 5124.56       0   78.92
Permanent Ineff=
       F       F
Bank Sta=4910.16,5114.56
Exp/Cntr=0.5,0.3

Type RM Length L Ch R = 3 ,7678.3  ,,,
BEGIN DESCRIPTION:
PL1_K111-00-00-S2
END DESCRIPTION:
Bridge Culvert--1,0,-1,-1, 0
Deck Dist Width WeirC Skew NumUp NumDn MinLoCord MaxHiCord MaxSubmerge Is_Ogee
10,2,2.6,0, 29, 29, , , 0.95, 0, ,,,
 4868.26  4869.6 4910.16 4911.47 4911.56 4924.46 4926.86 4945.26 4970.26 4985.36
 4986.56 4989.76 4991.86 5003.16 5007.96 5010.26 5013.76 5039.36 5042.76 5070.36
 5093.86 5098.56 5099.36 5104.26 5113.85 5113.96 5114.56  5135.5 5171.56
   79.69   79.69    80.9   80.94   80.94   81.33   81.33   81.33   81.33   81.33
   81.33   81.33   81.33   81.33   81.33   81.33   81.33   81.33   81.33   81.33
   81.33   81.33   81.33   81.28   80.95   80.94   80.92    80.2   78.92
                           78.86   78.94   79.33   79.33   79.33   79.33   79.33
   79.33   79.33   79.33   79.33   79.33   79.33   79.33   79.33   79.33   79.33
   79.33   79.33   79.33   79.28   78.95
 4868.26  4869.6 4910.16 4911.47 4911.56 4924.46 4926.86 4945.26 4970.26 4985.36
 4986.56 4989.76 4991.86 5003.16 5007.96 5010.26 5013.76 5039.36 5042.76 5070.36
 5093.86 5098.56 5099.36 5104.26 5113.85 5113.96 5114.56  5135.5 5171.56
   79.69   79.69    80.9   80.94   80.94   81.33   81.33   81.33   81.33   81.33
   81.33   81.33   81.33   81.33   81.33   81.33   81.33   81.33   81.33   81.33
   81.33   81.33   81.33   81.28   80.95   80.94   80.92    80.2   78.92
                           78.86   78.94   79.33   79.33   79.33   79.33   79.33
   79.33   79.33   79.33   79.33   79.33   79.33   79.33   79.33   79.33   79.33
   79.33   79.33   79.33   79.28   78.95
Pier Skew, UpSta & Num, DnSta & Num=  ,4926.9, 2 ,4926.9, 2 , 0 , 0 , 0 ,,
     1.4     1.4
   74.78   80.33
     1.4     1.4
   74.78   80.33
Pier Skew, UpSta & Num, DnSta & Num=  ,4985.4, 2 ,4985.4, 2 , 0 , 0 , 0 ,,
     1.4     1.4
   62.92   80.33
     1.4     1.4
   62.92   80.33
Pier Skew, UpSta & Num, DnSta & Num=  ,5042.8, 2 ,5042.8, 2 , 0 , 0 , 0 ,,
     1.4     1.4
   61.78   80.33
     1.4     1.4
   61.78   80.33
Pier Skew, UpSta & Num, DnSta & Num=  ,5098.6, 2 ,5098.6, 2 , 0 , 0 , 0 ,,
     1.4     1.4
   74.29   80.33
     1.4     1.4
   74.29   80.33
BR Coef= 1 , 1 , 1 ,1.25, 0 ,,,0.8,0,2,0,
WSPro=,,,, 1 ,,,, 0 ,,,, 0 ,,,,-1 ,-1 ,-1 , 0 , 0 , 0 , 0 , 0
BC Design=,, 0 ,, 0 ,,,,,,
BC HTab HWMax=87.1

Type RM Length L Ch R = 1 ,7667.0  ,65,69.4,69.4
BEGIN DESCRIPTION:
Downstream Section of Bridge/Culvert/Weir
END DESCRIPTION:
XS GIS Cut Line= 4
      3119082.67      13935269.8        3119472.     13935210.28
      3119931.15     13935128.94       3120700.9    13934978.382
#Sta/Elev= 30
  4313.3   81.55  4373.3   81.75  4403.3   80.15  4443.3   81.45  4603.3   81.25
 4765.16   79.29 4910.16   78.94 4926.86   75.86 4945.26   69.62 4970.26   63.52
 4985.36   64.21 4991.86    59.5 5003.16   59.07 5010.26   60.51 5013.76   63.32
 5042.76   62.62 5070.36   66.83 5098.56   75.37 5114.56   78.42 5171.56   78.76
  5283.1   82.04  5333.1   82.44  5422.7   80.85  5512.7   83.25  5562.7   82.75
  5712.7   86.95  5802.7   84.85  5892.7   85.65  5912.7   84.45  5962.7   85.65
#Mann= 6 ,-1 , 0
  4313.3     .07       0 4765.16    .045       0 4910.16     .04       0
 5114.56    .045       0 5171.56     .06       0  5333.1     .09       0
#XS Ineff= 2 , 0
       0 4903.49   79.18 5121.23       0   78.77
Permanent Ineff=
       F       F
Bank Sta=4910.16,5114.56
Exp/Cntr=0.5,0.3

Type RM Length L Ch R = 1 ,7597.6  ,99.1,99.1,99.1
BEGIN DESCRIPTION:
Upstream Section of Bridge/Culvert/Weir
END DESCRIPTION:
XS GIS Cut Line= 4
      3119051.29      13935343.5      3119482.21     13935277.41
      3120127.88      13935164.1      3120719.23      13935062.6
#Sta/Elev= 30
  4258.6    81.5  4318.6    81.2  4348.6    80.4  4468.6    79.5  4498.6      80
  4538.6    78.9  4558.6    78.9  4598.6    79.8  4618.6    78.7  4658.6    77.8
  4694.6    78.6  4698.9   79.02  4722.3   79.14  4818.1   79.63  4928.9   78.48
  4939.9   77.94  4946.9   75.75  4975.1   60.37  4979.9   60.29  5025.3   60.56
  5053.2   75.89    5060   77.96  5103.2    77.5  5168.9   78.23  5227.8   78.13
    5316   79.63  5520.1    82.5  5670.1    84.1  5710.1    83.7  5950.1    85.7
#Mann= 6 ,-1 , 0
  4258.6     .07       0  4722.3    .045       0  4939.9     .04       0
    5060    .045       0  5103.2     .06       0    5316     .09       0
#XS Ineff= 2 , 0
       0    4939    78.5    5060       0   81.68
Permanent Ineff=
       F       F
Bank Sta=4939.9,5060
Exp/Cntr=0.5,0.3

Type RM Length L Ch R = 3 ,7538.1  ,,,
BEGIN DESCRIPTION:
FM-1960; Also known as Humble-Westfield VRR
Structure ID: K111-00-00-S1
END DESCRIPTION:
Bridge Culvert--1,0,-1,-1, 0
Deck Dist Width WeirC Skew NumUp NumDn MinLoCord MaxHiCord MaxSubmerge Is_Ogee
10,78.6,2.6,0, 46, 46, , , 0.95, 0, ,,,
  4558.5  4568.5  4608.5  4618.5  4638.5  4668.5  4694.5  4698.9  4722.3  4762.9
  4814.6  4818.1 4851.89    4852 4852.11  4877.4  4928.9 4939.61  4939.7  4939.9
  4946.9  4974.6  4974.7  4975.1  4979.9  5009.2    5024  5025.2  5025.3  5053.2
 5059.29  5059.4    5060  5103.2 5147.19  5147.3 5147.41  5168.3  5168.9    5222
  5227.8  5280.4  5286.9    5316  5402.4    5430
    79.6    79.1    79.4    79.1    79.4    78.5    79.4   79.16   80.07   80.45
   81.64   81.64   81.63   82.83   82.83   82.83   82.84   82.84   82.84   82.84
   82.85   82.85   82.85   82.85   82.85   82.86   82.86   82.86   82.86   82.86
   82.87   82.87   82.87   82.87   82.88   82.88   81.68   81.76   81.76   82.11
   82.12    82.2   82.22    82.3   81.84    81.2
                                                                                
                                                                    78.9    78.9
   78.91   78.91   78.91   78.91   78.91   78.92   78.92   78.92   78.92   78.92
   78.93
                                                
  4558.5  4568.5  4608.5  4618.5  4638.5  4668.5  4694.5  4698.9  4722.3  4762.9
  4814.6  4818.1 4851.89    4852 4852.11  4877.4  4928.9 4939.61  4939.7  4939.9
  4946.9  4974.6  4974.7  4975.1  4979.9  5009.2    5024  5025.2  5025.3  5053.2
 5059.29  5059.4    5060  5103.2 5147.19  5147.3 5147.41  5168.3  5168.9    5222
  5227.8  5280.4  5286.9    5316  5402.4    5430
    79.6    79.1    79.4    79.1    79.4    78.5    79.4   79.16   80.07   80.45
   81.64   81.64   81.63   82.83   82.83   82.83   82.84   82.84   82.84   82.84
   82.85   82.85   82.85   82.85   82.85   82.86   82.86   82.86   82.86   82.86
   82.87   82.87   82.87   82.87   82.88   82.88   81.68   81.76   81.76   82.11
   82.12    82.2   82.22    82.3   81.84    81.2
                                                                                
                                                                    78.9    78.9
   78.91   78.91   78.91   78.91   78.91   78.92   78.92   78.92   78.92   78.92
   78.93
                                                
Pier Skew, UpSta & Num, DnSta & Num=  ,4979.9, 2 ,4979.9, 2 , 0 , 0 , 0 ,,
     1.3     1.3
   59.43   79.91
     1.3     1.3
   59.33   79.81
Pier Skew, UpSta & Num, DnSta & Num=  ,5020, 2 ,5020, 2 , 0 , 0 , 0 ,,
     1.3     1.3
   59.48   79.92
     1.3     1.3
   59.38   79.82
BR Coef= 1 , 1 , 1 ,1.25, 0 ,,,0.8,0,2,0,
WSPro=,,,, 1 ,,,, 0 ,,,, 0 ,,,,-1 ,-1 ,-1 , 0 , 0 , 0 , 0 , 0
BC Design=,, 0 ,, 0 ,,,,,,
BC HTab HWMax=85.7