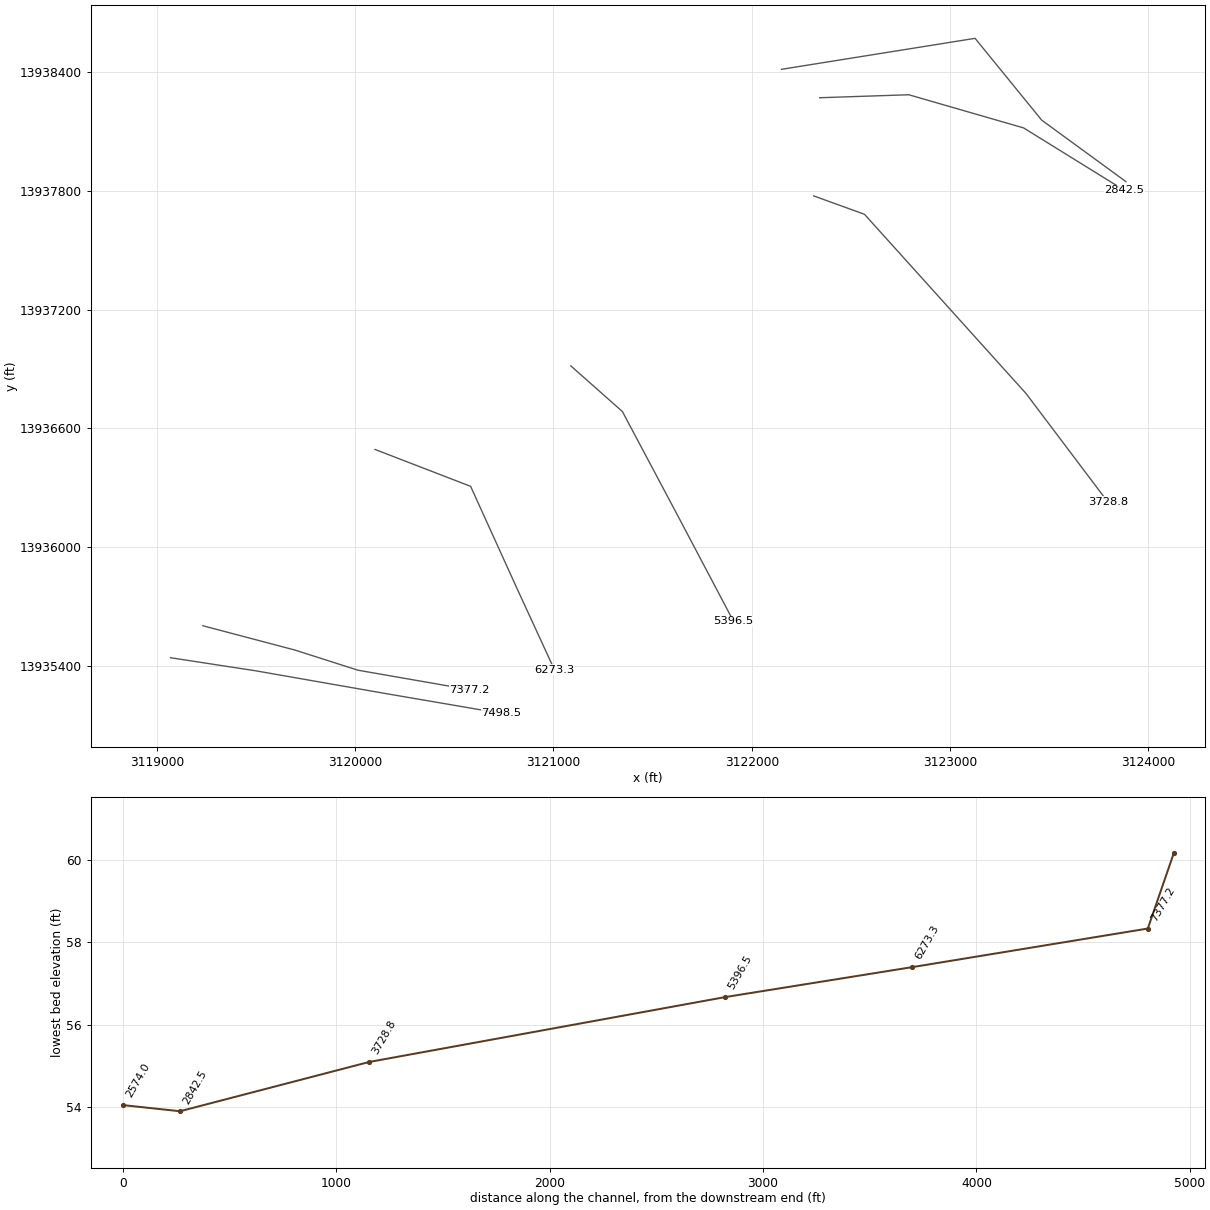
HEC-RAS study K111-00-00.prj: K111-00-00

--- K111-00-00.g02 (geometry) --- (continued)

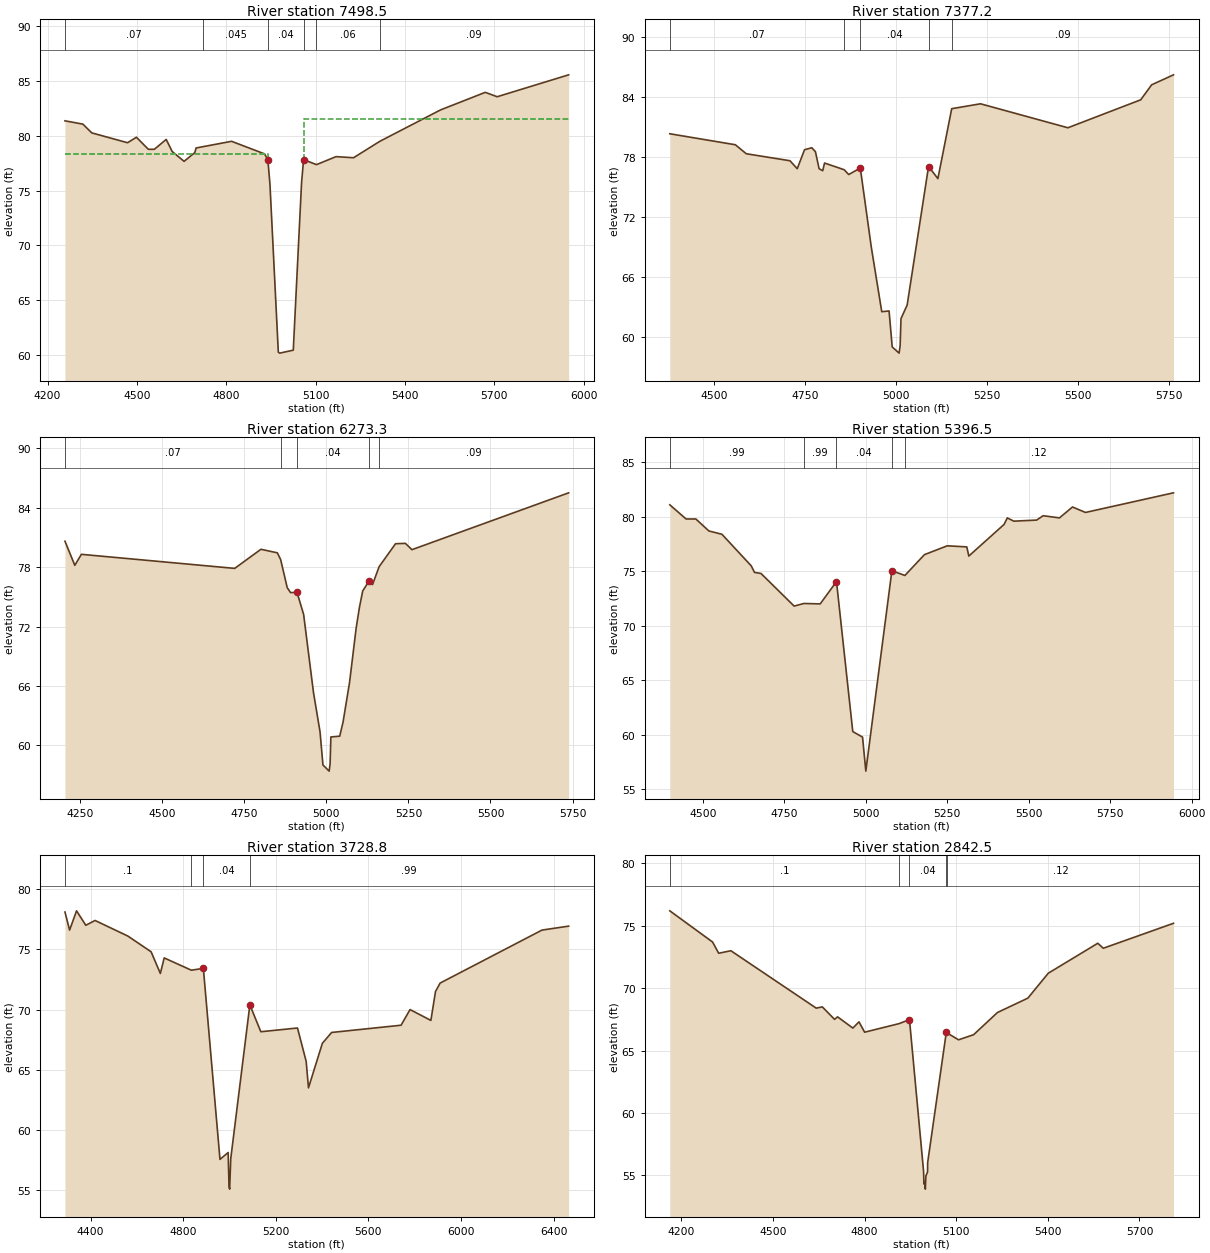
Type RM Length L Ch R = 1 ,7498.5  ,141,121.3,121.3
BEGIN DESCRIPTION:
Downstream Section of Bridge/Culvert/Weir
END DESCRIPTION:
XS GIS Cut Line= 4
      3119068.87      13935440.9      3119500.07     13935374.56
      3120145.98     13935261.21      3120737.27      13935159.7
#Sta/Elev= 30
  4258.6   81.38  4318.6   81.08  4348.6   80.28  4468.6   79.38  4498.6   79.88
  4538.6   78.78  4558.6   78.78  4598.6   79.68  4618.6   78.58  4658.6   77.68
  4694.6   78.48  4698.9    78.9  4722.3   79.02  4818.1   79.51  4928.9   78.36
  4939.9   77.82  4946.9   75.63  4975.1   60.25  4979.9   60.17  5025.3   60.44
  5053.2   75.77    5060   77.84  5103.2   77.38  5168.9   78.11  5227.8   78.01
    5316   79.51  5520.1   82.38  5670.1   83.98  5710.1   83.58  5950.1   85.58
#Mann= 6 ,-1 , 0
  4258.6     .07       0  4722.3    .045       0  4939.9     .04       0
    5060    .045       0  5103.2     .06       0    5316     .09       0
#XS Ineff= 2 , 0
       0    4939   78.38    5060       0   81.56
Permanent Ineff=
       F       F
Bank Sta=4939.9,5060
Exp/Cntr=0.5,0.3

Type RM Length L Ch R = 1 ,7377.2  ,1175,1103.9,1037
BEGIN DESCRIPTION:
Cross Section K111-00-00-X1a
END DESCRIPTION:
XS GIS Cut Line= 4
      3119232.36      13935602.4      3119695.99     13935479.73
      3120014.11     13935377.77      3120575.63      13935279.8
#Sta/Elev= 30
  4378.8    80.3  4558.8    79.2  4588.8    78.3  4708.8    77.6  4728.8    76.8
  4748.8    78.7  4768.8    78.9  4778.8    78.5  4788.8    76.8  4798.8    76.6
  4803.8   77.37  4857.6    76.7  4870.2   76.22    4902   76.87  4932.3   68.92
  4960.9   62.49    4981   62.56  4989.6   58.96  5008.5   58.34  5011.4   59.09
  5013.7   61.79  5030.7   63.16  5089.4   77.02  5115.1   75.81    5153   82.81
  5232.1    83.3  5472.1    80.9  5672.1    83.7  5702.1    85.2  5762.1    86.2
#Mann= 5 ,-1 , 0
  4378.8     .07       0  4857.6    .045       0    4902     .04       0
  5089.4    .045       0    5153     .09       0
Bank Sta=4902,5089.4
Exp/Cntr=0.3,0.1

Type RM Length L Ch R = 1 ,6273.3  ,876,876.8,876.8
BEGIN DESCRIPTION:
Interpolated XS
END DESCRIPTION:
XS GIS Cut Line= 4
      3120099.98      13936493.5      3120582.15     13936307.01
      3120812.19      13935799.2      3121004.23      13935381.2
#Sta/Elev= 30
  4203.6   80.61  4233.6   78.18  4253.6   79.29  4720.7   77.87  4800.7    79.8
  4850.7   79.44  4860.7   78.76  4880.7   75.93  4890.7   75.43  4910.7   75.44
  4930.7   73.22  4960.7   65.35  4980.7   61.37  4989.6   58.02  5008.5    57.4
  5011.4   58.15  5013.7   60.85  5040.7   60.93  5050.7   62.33  5070.7   66.37
  5090.7   71.83  5100.7   73.93  5110.7   75.59  5130.7   76.63  5140.7   76.24
  5160.7   78.04  5210.7   80.36  5240.7    80.4  5260.7   79.76  5738.2    85.5
#Mann= 5 ,-1 , 0
  4203.6     .07       0  4860.7    .045       0  4910.7     .04       0
  5130.7    .045       0  5160.7     .09       0
Bank Sta=4910.7,5130.7
Exp/Cntr=0.3,0.1

Type RM Length L Ch R = 1 ,5396.5  ,1638,1667.7,1801
BEGIN DESCRIPTION:
Cross Section K111-00-00-X4
END DESCRIPTION:
XS GIS Cut Line= 4
 3121087.581181813936915.6939012      3121347.64      13936684.9
      3121637.26     13936138.75 3121907.553311513935625.5053981
#Sta/Elev= 30
  4398.4    81.1  4448.4    79.8  4478.4    79.8  4518.4    78.7  4558.4    78.4
  4648.4    75.5  4658.4    74.9  4678.4    74.8    4780   71.81    4810   72.05
    4860   72.01    4910   74.06    4960    60.3    4990   59.79    5000   56.67
    5080   75.05    5120   74.62    5180   76.53    5250   77.34    5310   77.24
  5316.1    76.4  5424.3    79.3  5434.3    79.9  5454.3    79.6  5524.3    79.7
  5544.3    80.1  5594.3    79.9  5634.3    80.9  5674.3    80.4  5944.3    82.2
#Mann= 5 ,-1 , 0
  4398.4     .99       0    4810     .99       0    4910     .04       0
    5080    .045       0    5120     .12       0
Bank Sta=4910,5080
Exp/Cntr=0.3,0.1

Type RM Length L Ch R = 1 ,3728.8  ,855,886.3,1194
BEGIN DESCRIPTION:
Cross Section K111-00-00-X3
END DESCRIPTION:
XS GIS Cut Line= 4
      3122312.39      13937774.8      3122568.19     13937682.02
      3123383.27     13936775.92      3123795.22      13936228.3
#Sta/Elev= 30
  4289.2    78.1  4309.2    76.6  4339.2    78.2  4379.2      77  4419.2    77.4
  4561.3    76.1  4661.3    74.8  4701.3      73  4717.9   74.29  4835.1   73.27
  4887.1   73.42  4958.9   57.56  4994.2   58.13  4997.9   55.33  5000.7   55.09
  5005.4   57.61    5088   70.39  5135.4   68.16  5293.8   68.47  5331.3    65.7
  5341.3    63.5  5401.3    67.2  5441.3    68.1  5741.3    68.7  5780.1      70
  5870.1    69.1  5890.1    71.5    5910    72.2  6350.1    76.6  6465.4   76.93
#Mann= 4 ,-1 , 0
  4289.2      .1       0  4835.1    .045       0  4887.1     .04       0
    5088     .99       0
Bank Sta=4887.1,5088
Exp/Cntr=0.3,0.1

Type RM Length L Ch R = 1 ,2842.5  ,324,268.5,174
BEGIN DESCRIPTION:
Cross Section K111-00-00-X2
END DESCRIPTION:
XS GIS Cut Line= 4
      3122342.51       13938271.      3122791.61     13938286.09
      3123370.67     13938118.48      3123877.69     13937803.84
#Sta/Elev= 30
  4162.5    76.2  4302.5    73.7  4322.5    72.8  4362.5      73  4641.8    68.4
  4661.8    68.5  4701.8    67.5  4711.8    67.7  4761.8    66.8  4781.8    67.3
  4800.3   66.47  4913.5   67.16  4947.1   67.48  4993.3   55.31  4994.4    54.3
    4997   54.43    4999   53.89  5000.9   54.95  5006.3   55.27  5006.6   56.01
  5067.6   66.45  5070.9    66.4  5107.8   65.86  5157.1   66.27  5235.2   68.05
  5334.6    69.2  5401.6    71.2  5563.6    73.6  5581.6    73.2  5811.4    75.2
#Mann= 5 ,-1 , 0
  4162.5      .1       0  4913.5    .045       0  4947.1     .04       0
  5067.6    .045       0  5070.9     .12       0
Bank Sta=4947.1,5067.6
Exp/Cntr=0.3,0.1

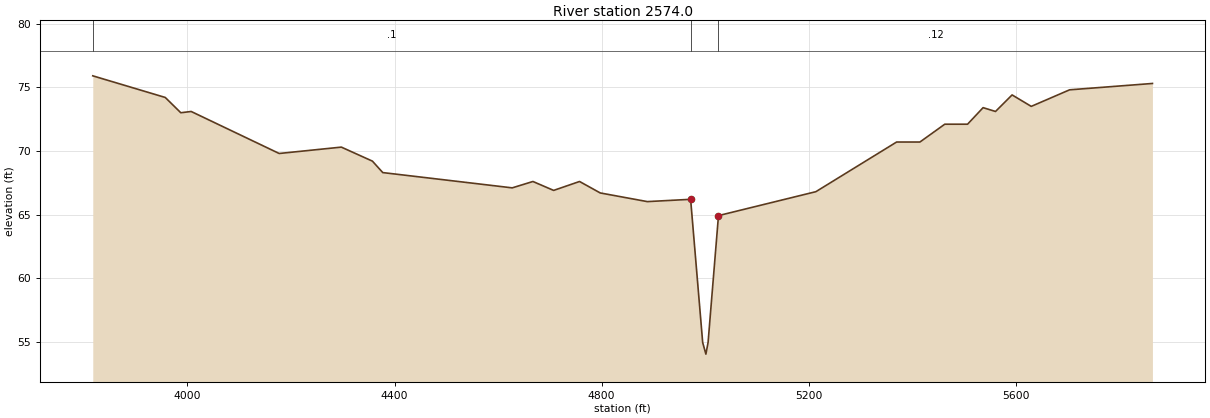
Type RM Length L Ch R = 1 ,2574.0  ,0,0,0
BEGIN DESCRIPTION:
Cross Section K111-00-00-X1
END DESCRIPTION:
XS GIS Cut Line= 5
       3122149.9      13938414.6      3122288.14      13938436.8
      3123125.96     13938571.19      3123461.88     13938157.83
      3123886.37     13937847.24
#Sta/Elev= 30
  3817.3    75.9  3957.3    74.2  3987.3      73  4007.3    73.1  4177.3    69.8
  4297.3    70.3  4357.3    69.2  4377.3    68.3  4627.3    67.1  4667.3    67.6
  4707.3    66.9  4757.3    67.6  4797.3    66.7  4888.2   66.02  4971.8    66.2
  4995.1   54.95  5001.3   54.04  5005.5   54.95  5025.6   64.92  5213.7    66.8
  5369.6    70.7  5414.6    70.7  5462.6    72.1  5506.6    72.1  5536.6    73.4
  5560.6    73.1  5592.6    74.4  5629.6    73.5  5703.6    74.8  5863.6    75.3
#Mann= 3 ,-1 , 0
  3817.3      .1       0  4971.8    .045       0  5025.6     .12       0
Bank Sta=4971.8,5025.6
Exp/Cntr=0.3,0.1

Chan Stop Cuts=-1
Use User Specified Reach Order=0
User Specified Reach Order=K111-00-00      ,K111-00-00_26